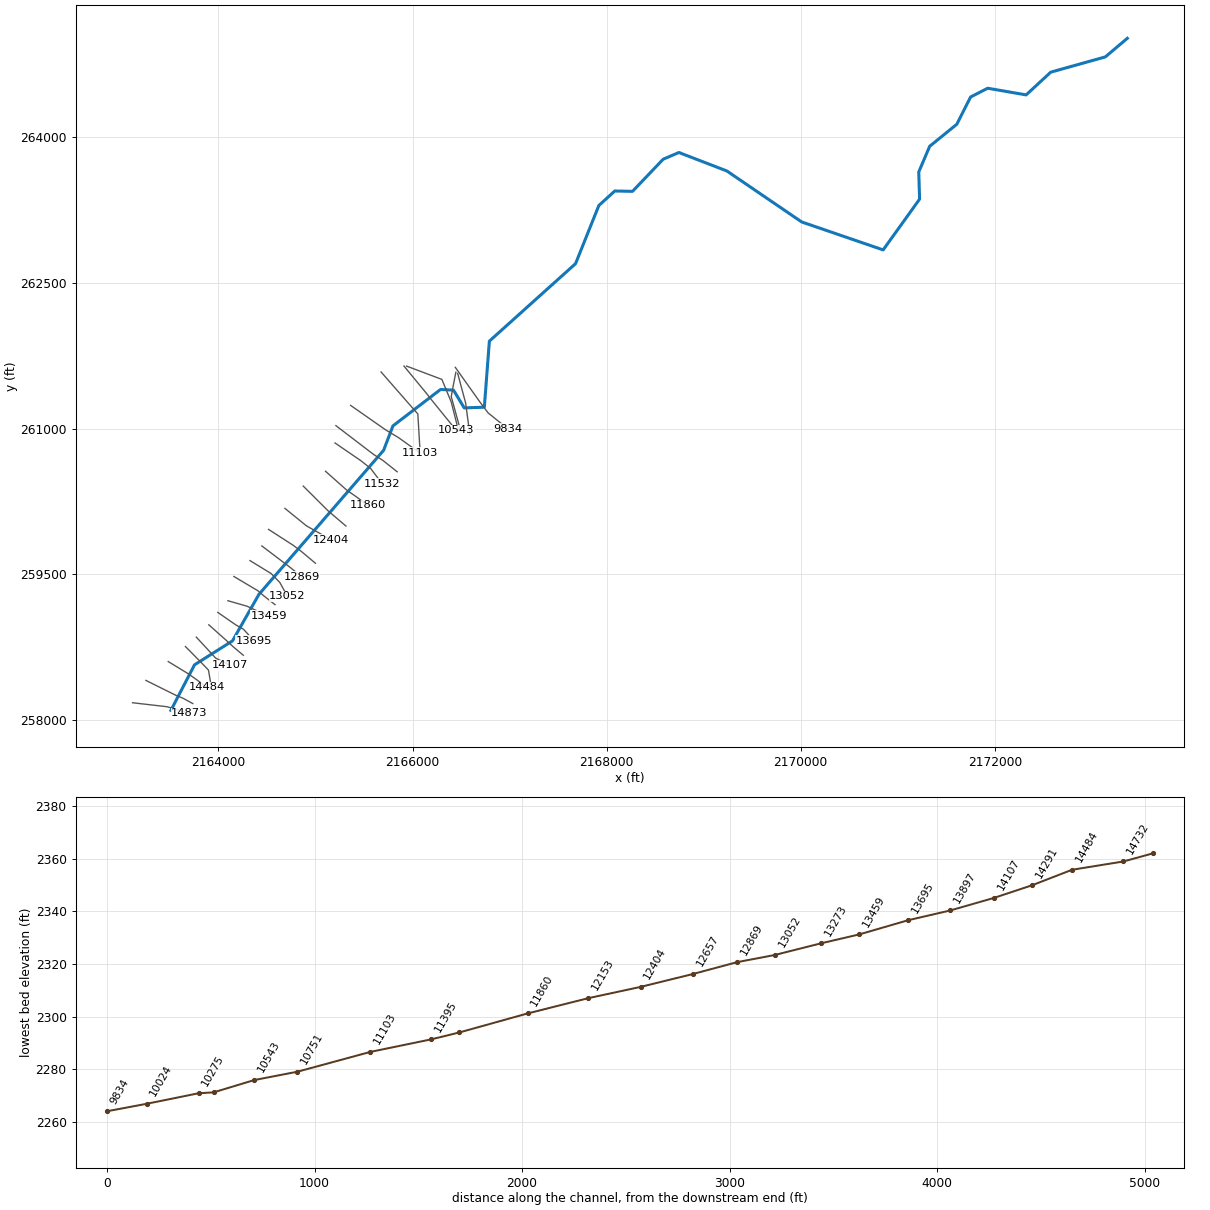
--- TUCKHORN.prj (project) ---

Proj Title=TUCKHORN
Current Plan=p01
Default Exp/Contr=0,0
English Units
Geom File=g01
Flow File=f01
Plan File=p01
Background Map Layer=DPs_HMS_shifted
Background Map Layer=QC_TUCKHORN
BEGIN DESCRIPTION:
Stream Name- Tuckahoe Run
Flood Zone: Zone A
Greenbrier County, WV
County-Wide Study
WVDHSEM-2018-3, Flood Risk Project
HEC-RAS Version: 5.0.7
General Notes:
For the Hydrology HECHMS 4.2.1 was used.
END DESCRIPTION:
DSS File=dss
DSS Export Rating Curves= 0
DSS Export Rating Curve Sorted= 0
DSS Export Volume Flow Curves= 0
DXF Filename=..\..\H1\MEADOWRV4\MEADOWRV4.
DXF OffsetX= 0
DXF OffsetY= 0
DXF ScaleX= 0
DXF ScaleY= 0

--- TUCKHORN.p01 (plan) ---

Plan Title=Floodplain
Program Version=5.07
Short Identifier=Floodplain
Geom File=g01
Flow File=f01
Subcritical Flow
K Sum by GR= 0
Std Step Tol= 0.01
Critical Tol= 0.01
Num of Std Step Trials= 20
Max Error Tol= 0.3
Flow Tol Ratio= 0.001
Split Flow NTrial= 30
Split Flow Tol= 0.02
Split Flow Ratio= 0.02
Log Output Level= 0
Friction Slope Method= 1
Unsteady Friction Slope Method= 2
Unsteady Bridges Friction Slope Method= 1
Parabolic Critical Depth
Global Vel Dist= 0 , 0 , 0
Global Log Level= 0
CheckData=True
Encroach Param=-1 ,0,0, 0
Computation Interval=0.1SEC
Output Interval=1MIN
Instantaneous Interval=Max Profile
Mapping Interval=1HOUR
Computation Time Step Use Courant=        0
Computation Time Step Use Time Series=    0
Computation Time Step Count To Double=0
Computation Time Step Max Doubling=0
Computation Time Step Max Halving=0
Computation Time Step Residence Courant=0
Run HTab= 0
Run UNet= 0
Run Sediment= 0
Run PostProcess= 0
Run WQNet= 0
Run RASMapper= 0
UNET Theta= 0
UNET Theta Warmup= 0
UNET ZTol= 0
UNET ZSATol= 0
UNET MxIter= 0
UNET Max Iter WO Improvement= 0
UNET MaxInSteps= 0
UNET DtIC= 0
UNET DtMin= 0
UNET MaxCRTS= 0
UNET WFStab= 0
UNET SFStab= 0
UNET WFX= 1
UNET SFX= 1
UNET 1D Methodology=Finite Difference
UNET DSS MLevel= 1
UNET Pardiso=0
UNET DZMax Abort= 0
UNET Use Existing IB Tables= 0
UNET Froude Reduction=False
UNET Froude Limit= 0
UNET Froude Power= 0
UNET D1 Cores= 0
UNET D2 Coriolis=0
UNET D2 Cores= 0
UNET D2 Theta= 1
UNET D2 Theta Warmup= 1
UNET D2 Z Tol= 0.01
UNET D2 Volume Tol= 0.01
UNET D2 Max Iterations= 20
UNET D2 Equation= 0
UNET D2 RampUpFraction=0.1
UNET D2 TimeSlices= 1
UNET D2 BCVolumeCheck=0
UNET D1D2 MaxIter= 0
UNET D1D2 ZTol=0.01
UNET D1D2 QTol=0.1
UNET D1D2 MinQTol=1
DSS File=dss
Write IC File= 0
Write IC File at Fixed DateTime=0
Write IC File at Sim End=0
Echo Input=False
Echo Parameters=False
Echo Output=False
Write Detailed= 0
HDF Write Warmup=0
HDF Write Time Slices=0
HDF Flush=0
HDF Face Node Velocities=0
HDF Compression= 1
HDF Chunk Size= 1
HDF Spatial Parts= 1
HDF Use Max Rows=0
HDF Fixed Rows= 1
Calibration Method= 0
Calibration Iterations= 20
Calibration Max Change=0.05
Calibration Tolerance=0.2
Calibration Maximum=1.5
Calibration Minimum=0.5
Calibration Optimization Method= 1
WQ AD Non Conservative
WQ ULTIMATE=-1
WQ Max Comp Step=1HOUR
WQ Output Interval=15MIN
WQ Output Selected Increments= 0
WQ Output face flow=0
WQ Output face velocity=0
WQ Output face area=0
WQ Output face dispersion=0
WQ Output cell volume=0
WQ Output cell surface area=0
WQ Output cell continuity=0
WQ Output cumulative cell continuity=0
WQ Output face conc=0
WQ Output face dconc_dx=0
WQ Output face courant=0
WQ Output face peclet=0
WQ Output face adv mass=0
WQ Output face disp mass=0
WQ Output cell mass=0
WQ Output cell source sink temp=0
WQ Output nsm pathways=0
WQ Output nsm derived pathways=0
WQ Output MaxMinRange=-1
WQ Daily Max Min Mean=-1
WQ Daily Range=0
WQ Daily Time=0
WQ Create Restart=0
WQ Fixed Restart=0
WQ System Summary=0
WQ Write To DSS=0
WQ Use Fixed Temperature=0
Sorting and Armoring Iterations= 10
XS Update Threshold= 0.02
Bed Roughness Predictor= 0
Hydraulics Update Threshold= 0.02
Energy Slope Method= 1
Volume Change Method= 1
Sediment Retention Method= 0
XS Weighting Method= 0
Number of US Weighted Cross Sections= 1
Number of DS Weighted Cross Sections= 1
Upstream XS Weight=0
Main XS Weight=1
Downstream XS Weight=0
Number of DS XS's Weighted with US Boundary= 1
Upstream Boundary Weight= 1
Weight of XSs Associated with US Boundary= 0
Number of US XS's Weighted with DS Boundary= 1
Downstream Boundary Weight= 0.5
Weight of XSs Associated with DS Boundary= 0.5
Percentile Method= 0
Sediment Output Level= 3
Mass or Volume Output= 0
Output Increment Type= 1
Profile and TS Output Increment= 1
XS Output Flag= 0
XS Output Increment= 10
Write Gradation File= 0
Read Gradation Hotstart= 0
Write HDF5 File= 1
Write Binary Output= 1
Write DSS Sediment File= 0
SV Curve= 0
Specific Gage Flag= 0

--- TUCKHORN.f01 (steady flow) ---

Flow Title=MasterFlow
Program Version=5.07
Number of Profiles= 6
Profile Names=f1p,f10p,f4p,f2p,f02p,f1pplus
River Rch & RM=TUCKHORN,Main            ,14873
     566     299     398     479     791     837
River Rch & RM=TUCKHORN,Main            ,12657
     639     339     450     542     891     945
River Rch & RM=TUCKHORN,Main            ,10275
    1150     622     817     976    1580    1700
River Rch & RM=TUCKHORN,Main            ,6291
    1390     758     991    1180    1900    2050
River Rch & RM=TUCKHORN,Main            ,4342
    1770     980    1280    1520    2430    2620
River Rch & RM=TUCKHORN,Main            ,346
    2140    1190    1540    1830    2910    3160
River Rch & RM=TUCKHORN,Main            ,239
    3116    1352    1964    2514    4764    3780
Boundary for River Rch & Prof#=TUCKHORN,Main            , 1
Up Type= 0
Dn Type= 1
Dn Known WS=2122.5
Boundary for River Rch & Prof#=TUCKHORN,Main            , 2
Up Type= 0
Dn Type= 1
Dn Known WS=2120.44
Boundary for River Rch & Prof#=TUCKHORN,Main            , 3
Up Type= 0
Dn Type= 1
Dn Known WS=2121
Boundary for River Rch & Prof#=TUCKHORN,Main            , 4
Up Type= 0
Dn Type= 1
Dn Known WS=2121.64
Boundary for River Rch & Prof#=TUCKHORN,Main            , 5
Up Type= 0
Dn Type= 1
Dn Known WS=2124.99
Boundary for River Rch & Prof#=TUCKHORN,Main            , 6
Up Type= 0
Dn Type= 1
Dn Known WS=2123.27
DSS Import GetInterval= 0
DSS Import GetPeak= 0
DSS Import FillOption= 0

--- TUCKHORN.g01 (geometry) ---

Geom Title=MasterGeometry
Program Version=5.07

River Reach=TUCKHORN        ,Main
Reach XY= 30
     2163510.565       258095.55     2163754.128      258565.362
     2164145.245      258812.024     2164418.513      259292.279
     2165702.386      260775.599     2165798.345      261027.196
     2166289.245      261402.541     2166422.524        261395.4
     2166533.006      261212.382     2166740.162      261219.781
      2166792.06      261900.478     2167680.071      262698.835
     2167920.042      263297.852     2168084.239      263447.441
      2168267.02      263443.704     2168582.149       263774.29
     2168744.823      263843.985     2169239.392      263653.347
     2170009.635      263128.604     2170849.246      262840.376
     2171224.766       263363.64      2171216.05      263643.476
      2171328.46      263907.7452171607.99099468264134.877231179
2171750.16711426264415.699545624     2171926.154      264506.159
     2172322.557      264437.532      2172576.11      264671.686
2173138.29614398264828.9137752822173364.96770971265020.247552186

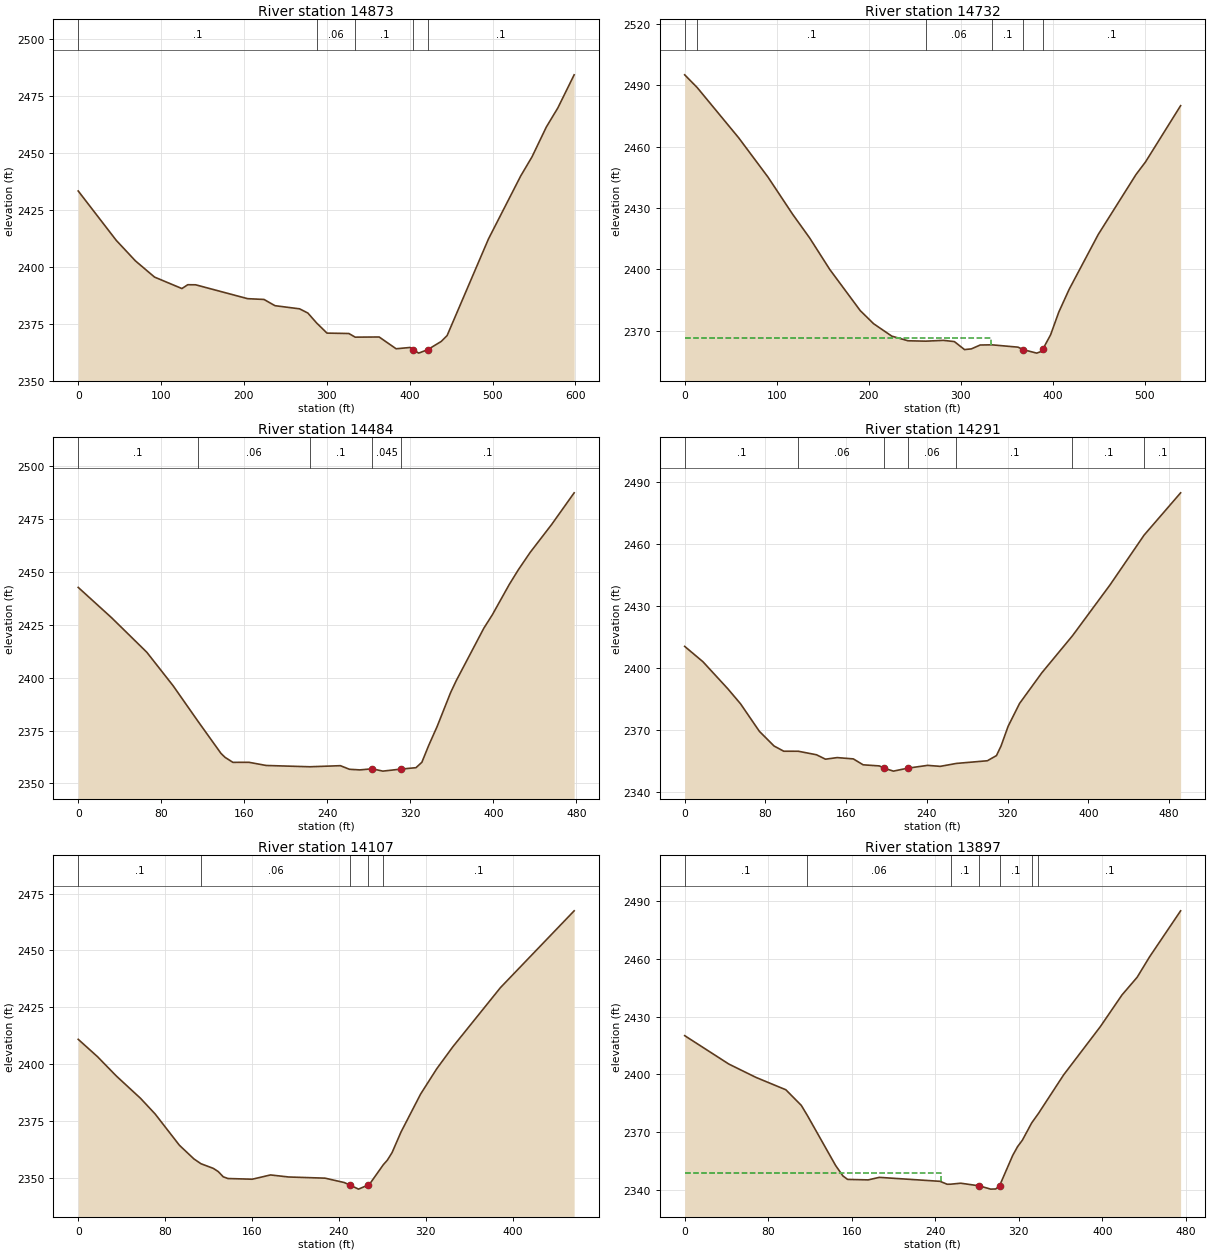
Type RM Length L Ch R = 1 ,14873   ,141,141,141
XS GIS Cut Line= 4
2163115.70540876258174.6161956912163469.26470943258133.874410945
2163567.33484984 258106.576536812163701.80215576258065.124209421
#Sta/Elev= 30
       0 2433.35    45.9 2411.64      69 2402.62    92.1 2395.48   125.1 2390.44
   132.2 2392.12   141.7 2392.09   204.4 2385.99   224.2 2385.64   237.4 2382.91
   267.1 2381.52   277.1 2379.67  287.692375.295   300.2 2370.84   326.6 2370.67
   334.22369.064   363.1 2369.14   383.6 2363.96   400.6 2364.53  404.462363.536
   410.8 2362.04  421.532363.535   438.1  2367.2   445.1 2369.75   495.1 2412.31
     534    2440   547.6 2448.39   564.9 2461.52   578.7 2469.86 598.409 2484.43
#Mann= 5 ,-1 , 0
       0      .1       0  287.69     .06       0   334.2      .1       0
  404.46    .045       0  421.53      .1       0
Bank Sta=404.46,421.53
XS Rating Curve= 0 ,0
Exp/Cntr(USF)=0,0
Exp/Cntr=0.3,0.1

Type RM Length L Ch R = 1 ,14732   ,247.7,247.7,247.7
XS GIS Cut Line= 4
 2163252.9037811258404.8310875392163566.32381746258249.132101735
2163634.06298661  258221.83422762163736.17725652258166.227446956
#Sta/Elev= 30
       0 2495.11   13.532488.927    58.8 2464.26    90.6 2445.08   117.5 2426.84
   135.8 2415.38   157.8 2399.89   190.9 2379.78   205.4 2373.38   225.2 2367.29
   242.9 2365.02  262.282364.831   281.5 2365.23   293.3 2364.61   304.3 2360.71
   311.7 2361.05   321.3 2362.95  334.02 2363.04   362.5  2361.9   368.1  2360.7
   382.8 2358.98   387.3 2359.72  389.682361.102   397.9 2367.95   406.8 2379.05
   418.1 2390.22   449.7 2417.02   490.8 2446.37   501.1 2452.51 539.269 2480.03
#Mann= 6 ,-1 , 0
       0      .1       0   13.53      .1       0  262.28     .06       0
  334.02      .1       0   368.1    .045       0  389.68      .1       0
#XS Ineff= 2 , 0
          333.51 2366.31
Permanent Ineff=
       F       F
Bank Sta=368.1,389.68
XS Rating Curve= 0 ,0
Exp/Cntr(USF)=0,0
Exp/Cntr=0.3,0.1

Type RM Length L Ch R = 1 ,14484   ,193.7,193.7,193.7
XS GIS Cut Line= 4
2163483.41916268258598.9493036062163690.68079963258472.570256687
2163770.55235728258415.952443668 2163880.7548862258334.058821264
#Sta/Elev= 30
       0  2442.6    32.2 2428.26    66.1 2411.98    91.5 2396.13   115.62379.258
   137.6  2364.2   141.5 2362.34   149.1 2359.97   164.5    2360   181.2  2358.5
  223.312357.888   252.7  2358.4   261.4  2356.7   271.5 2356.41   283.3 2356.94
   293.6 2355.83   311.5 2356.82   325.5 2357.45   331.2 2360.01   337.8 2367.99
   345.9  2376.9   358.9 2392.94   364.4 2398.63   390.9 2423.32   399.1 2429.66
   415.4 2443.96   424.2 2450.94   435.6 2459.15   456.3 2472.33477.9558 2487.26
#Mann= 5 ,-1 , 0
       0      .1       0   115.6     .06       0  223.31      .1       0
   283.3    .045       0   311.5      .1       0
Bank Sta=283.3,311.5
XS Rating Curve= 0 ,0
Exp/Cntr(USF)=0,0
Exp/Cntr=0.3,0.1

Type RM Length L Ch R = 1 ,14291   ,183.2,183.2,183.2
XS GIS Cut Line= 4
2163660.34982837258753.6372570352163791.78403717258621.192015864
2163897.94243658258510.9894869512163923.21824596258361.356695399
#Sta/Elev= 30
       0 2410.31    18.1 2402.88    42.8 2389.76    55.4 2382.48      74  2369.2
    88.5  2362.1    98.2 2359.55  112.572359.545   130.6 2357.84   139.5  2355.7
   151.1 2356.47   167.1 2355.84   176.8 2352.98   192.9 2352.44  197.812351.331
   206.8 2349.92  220.772351.329   240.7 2352.71   253.2 2352.23  269.192353.647
   299.9 2354.94   308.9 2357.44   313.4 2362.03   320.5 2371.67   331.8 2382.69
   353.9 2397.55  384.232415.464   421.5 2440.13  455.212464.196491.3619 2484.65
#Mann= 7 ,-1 , 0
       0      .1       0  112.57     .06       0  197.81    .045       0
  220.77     .06       0  269.19      .1       0  384.23      .1       0
  455.21      .1       0
Bank Sta=197.81,220.77
XS Rating Curve= 0 ,0
Exp/Cntr(USF)=0,0
Exp/Cntr=0.3,0.1

Type RM Length L Ch R = 1 ,14107   ,210.7,210.7,210.7
XS GIS Cut Line= 4
2163772.57442204258850.6963650692163925.24031071258685.898087886
 2163970.7367676258635.3464691192164117.33646203258561.541105718
#Sta/Elev= 30
       0 2410.94    17.8  2403.3      35 2394.88    57.4 2385.02    70.8 2378.18
    93.2 2364.41   106.6 2358.39  113.042356.295   124.5 2354.23     129 2352.83
   133.6 2350.54   137.9 2349.79   160.3 2349.48   177.1 2351.36   193.9 2350.46
   227.3 2349.95     245 2348.03  250.442346.873   258.2 2345.13  266.682346.872
   269.5 2348.09  281.072355.889   284.7 2357.83   289.1  2361.2   297.3 2370.21
   315.4 2386.92   330.2 2397.99   345.1 2407.69   388.9 2433.65456.7853 2467.39
#Mann= 5 ,-1 , 0
       0      .1       0  113.04     .06       0  250.44    .045       0
  266.68     .06       0  281.07      .1       0
#XS Ineff= 2 , 0
          176.19 2350.09
Permanent Ineff=
       F       F
Bank Sta=250.44,266.68
XS Rating Curve= 0 ,0
Exp/Cntr(USF)=0,0
Exp/Cntr=0.3,0.1

Type RM Length L Ch R = 1 ,13897   ,201.6,201.6,201.6
XS GIS Cut Line= 4
 2163900.9755337258978.086444363 2164098.1268469258802.166811052
2164154.74465992258749.5931275342164256.85892983258663.655375629
#Sta/Elev= 30
       0 2420.13    42.3 2405.36    68.3 2398.42    96.9    2392   111.7 2383.88
  117.522378.632   144.5  2352.7   151.5 2347.26     156 2345.43   175.7 2345.17
   186.4 2346.48   244.5 2344.43   251.4  2342.9  254.632342.933   264.4 2343.44
  281.922342.095   293.1 2340.37   297.9 2340.46  301.542342.094   314.1 2357.83
   318.8 2362.44   323.4  2365.8  332.342374.792  338.812379.703   362.9 2399.73
   398.1 2424.83   418.8 2441.27   433.3 2450.45   445.2 2461.06474.9548 2484.99
#Mann= 7 ,-1 , 0
       0      .1       0  117.52     .06       0  254.63      .1       0
  281.92    .045       0  301.54      .1       0  332.34      .1       0
  338.81      .1       0
#XS Ineff= 2 , 0
          245.45 2348.65
Permanent Ineff=
       F       F
Bank Sta=281.92,301.54
XS Rating Curve= 0 ,0
Exp/Cntr(USF)=0,0
Exp/Cntr=0.3,0.1

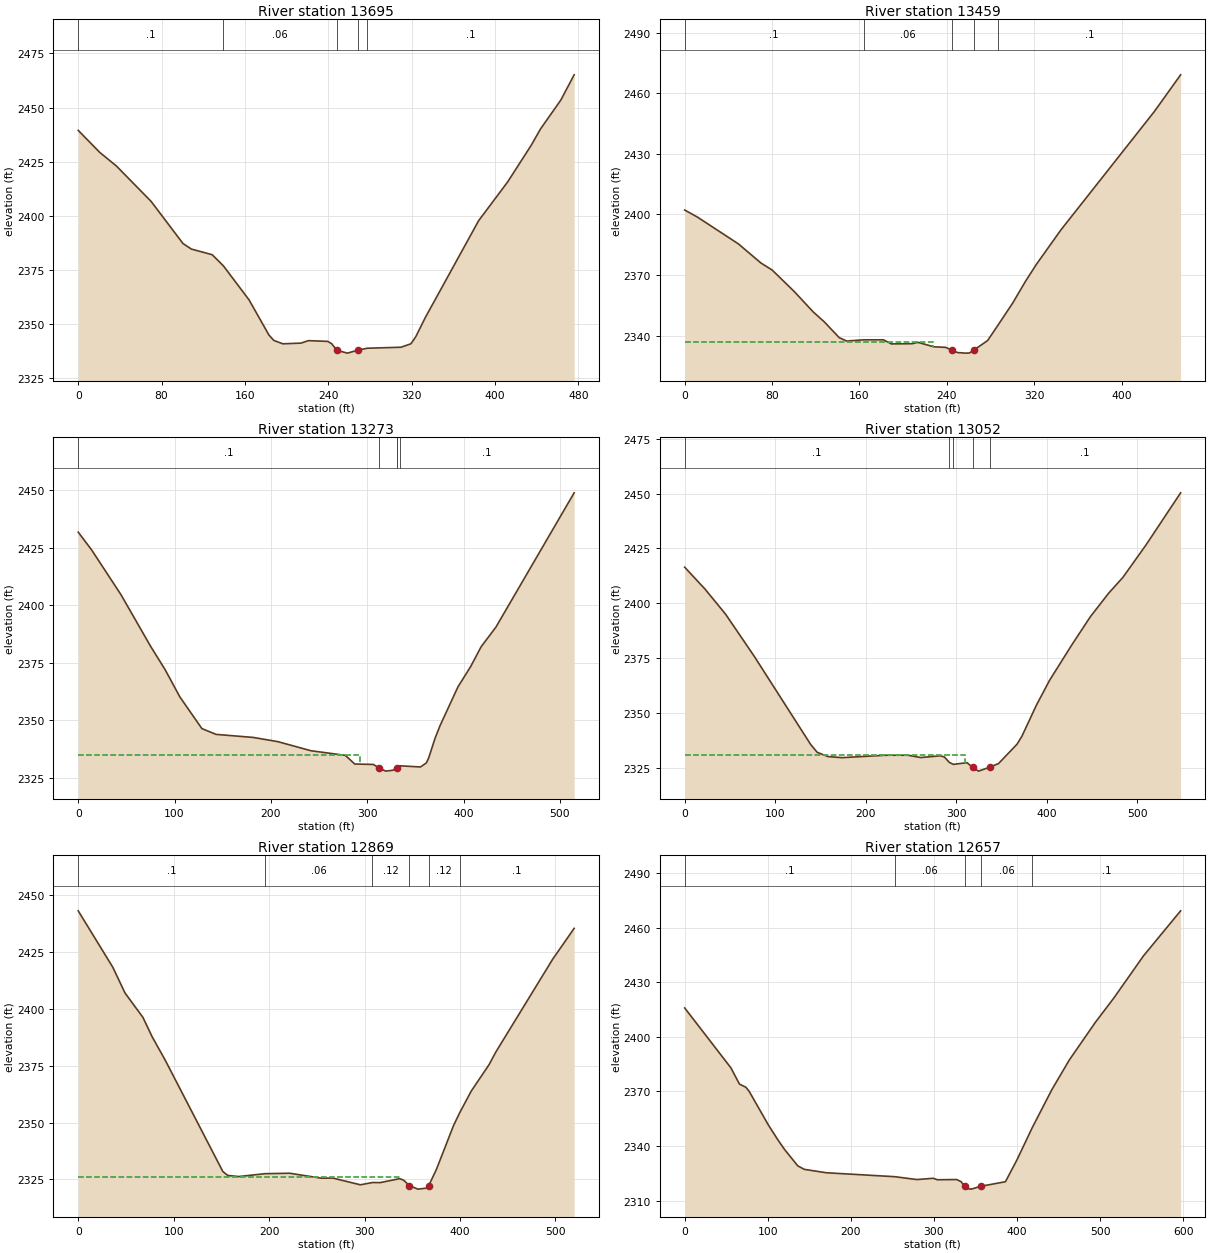
Type RM Length L Ch R = 1 ,13695   ,236.1,236.1,236.1
XS GIS Cut Line= 4
2163993.99051224259105.4765236572164179.00943693258977.075411988
2164258.88099458258931.5789550972164366.05042637258814.299199556
#Sta/Elev= 30
       0  2439.5    20.7 2429.32    36.7 2423.04      70  2406.7   100.6 2387.25
   108.6 2384.72   128.6 2382.11  139.442376.918     164 2361.24   183.1 2345.02
   187.8 2342.54   196.4 2340.99   213.8 2341.31   220.9 2342.45   239.5 2342.11
   243.3 2341.04  248.24    2338   258.4 2336.69  268.112338.003  277.32 2338.95
   309.8 2339.41   319.3    2341     324 2344.27   333.2 2353.16   384.3 2397.79
   412.2 2415.72   434.9  2432.7   443.7 2440.14   463.3 2453.55475.9995 2465.13
#Mann= 5 ,-1 , 0
       0      .1       0  139.44     .06       0  248.24    .045       0
  268.11     .06       0  277.32      .1       0
Bank Sta=248.24,268.11
XS Rating Curve= 0 ,0
Exp/Cntr(USF)=0,0
Exp/Cntr=0.3,0.1

Type RM Length L Ch R = 1 ,13459   ,185.5,185.5,185.5
XS GIS Cut Line= 4
 2164098.1268469259225.7893763242164295.27816009259169.171563304
2164391.32623575259124.6861387892164522.76044455259068.068325769
#Sta/Elev= 30
       0  2402.2    11.8 2398.66    49.3 2385.38    69.8 2375.95      80 2372.51
   100.5 2361.73   117.6 2351.75   127.8 2346.81   141.5 2338.96   148.3 2337.28
  163.752337.879     182 2337.88   189.3 2335.86   208.2 2335.95   213.6 2336.63
   228.1 2334.43     239 2334.15  244.472332.807   249.8 2331.58     257 2331.29
   260.6 2331.34  264.832332.805   277.4 2337.54  286.912345.189   300.4 2356.15
     312 2366.83   322.1 2375.33   344.5 2392.36     430 2450.98  454.08 2469.19
#Mann= 5 ,-1 , 0
       0      .1       0  163.75     .06       0  244.47    .045       0
  264.83     .06       0  286.91      .1       0
#XS Ineff= 2 , 0
          227.27 2336.94
Permanent Ineff=
       F       F
Bank Sta=244.47,264.83
XS Rating Curve= 0 ,0
Exp/Cntr(USF)=0,0
Exp/Cntr=0.3,0.1

Type RM Length L Ch R = 1 ,13273   ,221.5,221.5,221.5
XS GIS Cut Line= 4
 2164159.7998218259475.5143730362164406.49172138 259328.91467861
 2164471.1977934259273.3078979662164583.42238707 259185.34808131
#Sta/Elev= 30
       0 2431.82    13.9 2424.11    44.5 2404.56      75 2382.29    90.3 2371.96
   105.5 2360.19   128.4 2346.39   143.1 2343.87   181.6 2342.55   207.3 2340.71
   241.6 2336.76   277.3 2334.75   287.1 2330.98   306.3  2330.8     3122329.377
   319.2 2327.89   326.6 2328.27  330.592329.375  330.862329.468  333.572330.213
   355.4  2329.7   361.5  2331.5   363.9 2333.68   370.5 2342.23   375.5 2347.53
   394.2  2364.5   407.6 2373.49   418.3 2381.98   433.7 2390.55514.8689 2448.92
#Mann= 5 ,-1 , 0
       0      .1       0     312    .045       0  330.59      .1       0
  330.86     .06       0  333.57      .1       0
#XS Ineff= 2 , 0
          292.47 2334.82
Permanent Ineff=
       F       F
Bank Sta=312,330.59
XS Rating Curve= 0 ,0
Exp/Cntr(USF)=0,0
Exp/Cntr=0.3,0.1

Type RM Length L Ch R = 1 ,13052   ,183,183,183
XS GIS Cut Line= 4
2164325.60913135259639.301617843 2164545.0031568259504.834311921
2164632.96297346259413.8413981392164711.82349874259270.274800839
#Sta/Elev= 30
       0 2416.43    22.2 2406.57    45.2    2395    77.1 2375.65   139.1 2335.65
   146.3 2332.07   158.2 2330.12   173.6 2329.62   222.6 2330.73   246.7 2330.71
   260.7 2329.67   282.1 2330.46   286.8 2329.95  292.192327.495  296.632326.564
   311.8 2327.32  317.872325.258   324.5 2323.48  336.752325.258   346.6 2326.93
     367 2335.74   372.4 2339.36   388.5  2353.6     403 2364.89   427.7 2381.13
   448.1  2393.9   468.2 2404.57     484 2411.81   509.5 2426.59547.6797 2450.32
#Mann= 5 ,-1 , 0
       0      .1       0  292.19     .06       0  296.63      .1       0
  317.87    .045       0  336.75      .1       0
#XS Ineff= 2 , 0
          309.61 2330.72
Permanent Ineff=
       F       F
Bank Sta=317.87,336.75
XS Rating Curve= 0 ,0
Exp/Cntr(USF)=0,0
Exp/Cntr=0.3,0.1

Type RM Length L Ch R = 1 ,12869   ,211.6,211.6,211.6
XS GIS Cut Line= 4
2164447.94404877 259789.945441772164690.59181885259605.937549456
2164749.23169662259561.4521249412164858.42319316259471.470243534
#Sta/Elev= 30
       0  2443.2    36.3 2418.34      49 2407.07    67.8 2396.32    77.5 2387.77
    91.2 2377.46   151.6 2328.44   156.8 2326.76   168.1 2326.28  195.812327.534
   221.6 2327.73   254.6 2325.56   266.9 2325.59   295.7 2322.64  308.26 2323.65
   316.3  2323.6   336.9 2325.35     341 2324.66   346.92322.314   355.8 2320.74
   365.2 2321.18  367.312322.316   375.3 2329.41   393.2 2348.68  399.522354.201
   411.8 2363.88   430.5 2375.53   437.6  2381.1   497.1 2421.89519.6219 2435.49
#Mann= 6 ,-1 , 0
       0      .1       0  195.81     .06       0  308.26     .12       0
   346.9    .045       0  367.31     .12       0  399.52      .1       0
#XS Ineff= 2 , 0
          337.14 2325.99
Permanent Ineff=
       F       F
Bank Sta=346.9,367.31
XS Rating Curve= 0 ,0
Exp/Cntr(USF)=0,0
Exp/Cntr=0.3,0.1

Type RM Length L Ch R = 1 ,12657   ,253.1,253.1,253.1
XS GIS Cut Line= 4
2164516.69425029259960.8099132042164770.46337651259797.022668397
2164845.27977228259741.4158877532164999.96772571259612.003743708
#Sta/Elev= 30
       0 2415.91    55.7 2382.92    65.9 2374.05    73.7 2372.28    77.6 2370.06
     101 2351.33   112.7 2343.02   120.5  2337.9   136.2 2329.04     144 2327.13
   170.6 2325.26  252.992323.096   279.5 2321.52   299.2 2322.23   304.2 2321.41
   327.4 2321.54   332.8 2320.32  336.822317.804     341 2316.48     345 2316.26
  356.222317.804   386.1 2320.33     400  2332.4  418.192349.907   441.9 2370.93
   462.9 2387.24   494.1 2407.85   516.5 2421.33   552.3 2444.57596.9355 2469.31
#Mann= 5 ,-1 , 0
       0      .1       0  252.99     .06       0  336.82    .045       0
  356.22     .06       0  418.19      .1       0
Bank Sta=336.82,356.22
XS Rating Curve= 0 ,0
Exp/Cntr(USF)=0,0
Exp/Cntr=0.3,0.1

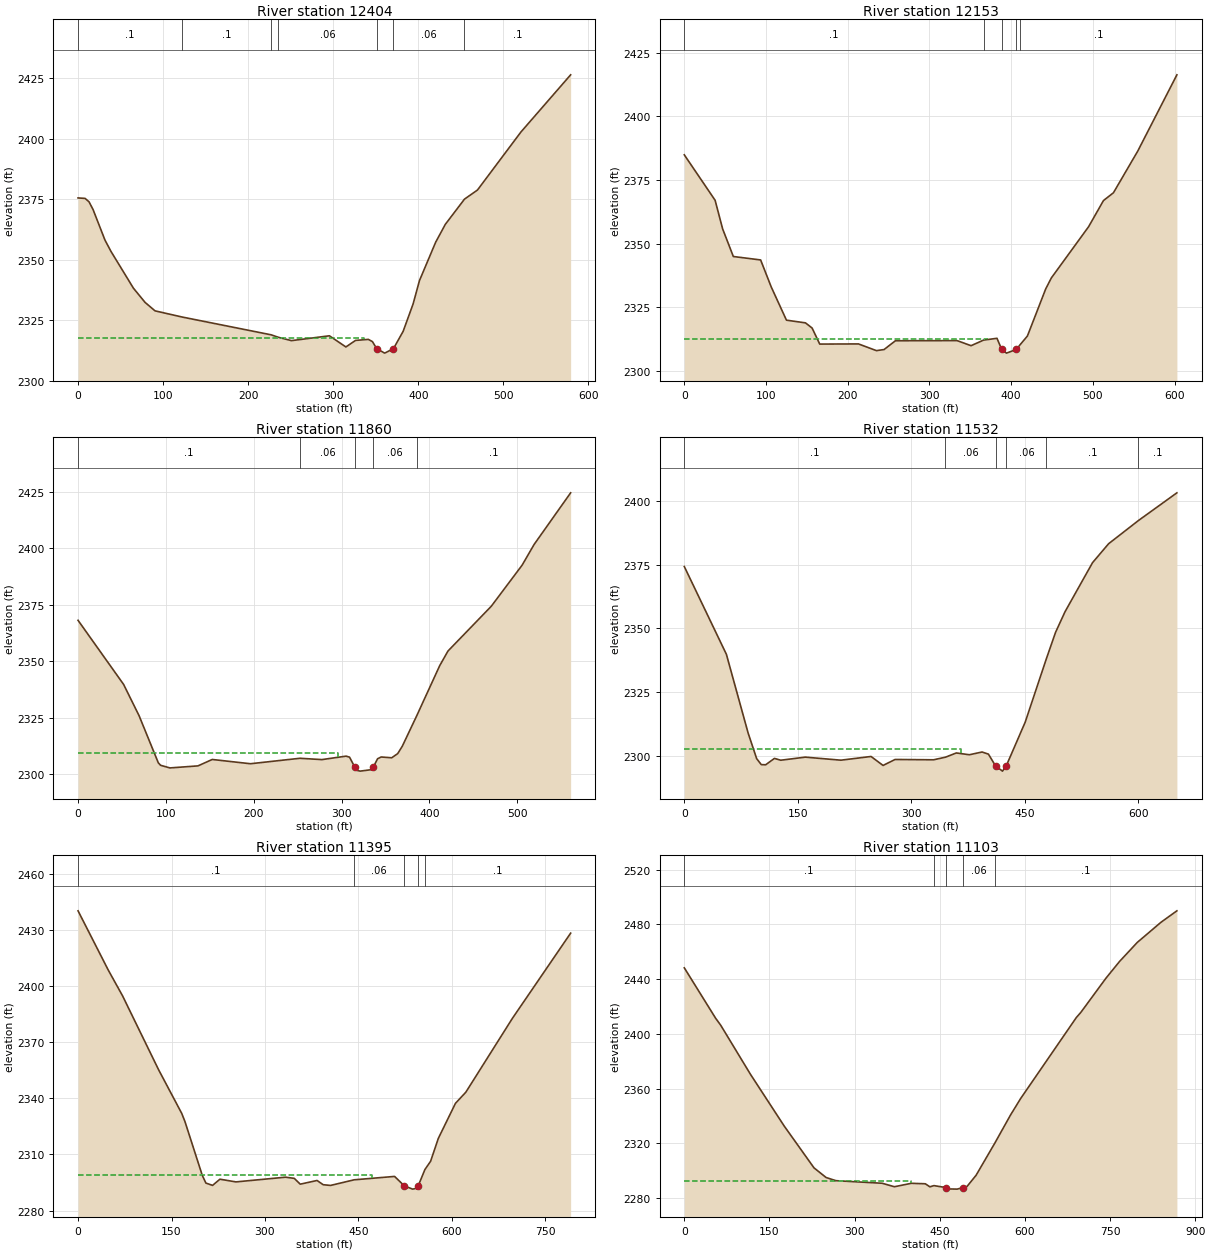
Type RM Length L Ch R = 1 ,12404   ,250.9,250.9,250.9
XS GIS Cut Line= 3
2164685.53665698 260177.17084153 2164905.9417148259998.218111092
2165162.74393814259852.629449042
#Sta/Elev= 30
       0  2375.5     8.3 2375.31    12.9 2373.89    17.6 2370.75    31.6 2358.13
    38.6 2353.47    65.1  2338.2    78.8 2332.32    90.5 2328.83  121.852326.311
  227.072318.915   235.52317.897   250.9 2316.51   295.5 2318.52   314.9  2313.9
   326.2  2316.6   341.3 2317.03   346.1 2316.11  351.122313.192   360.5 2311.35
   370.82313.195   382.2 2320.36   393.9 2331.67   401.4 2341.35   420.5 2357.25
   431.8 2364.59  454.322375.006   469.6 2378.78   520.7 2402.77579.1064 2426.39
#Mann= 7 ,-1 , 0
       0      .1       0  121.85      .1       0  227.07      .1       0
   235.5     .06       0  351.12    .045       0   370.8     .06       0
  454.32      .1       0
#XS Ineff= 2 , 0
           336.1 2317.66
Permanent Ineff=
       F       F
Bank Sta=351.12,370.8
XS Rating Curve= 0 ,0
Exp/Cntr(USF)=0,0
Exp/Cntr=0.3,0.1

Type RM Length L Ch R = 1 ,12153   ,293.3,293.3,293.3
XS GIS Cut Line= 3
2164874.59971117260406.6751907342165132.41296688260149.872967395
2165314.39879445259995.185013966
#Sta/Elev= 30
       0 2384.89    37.7 2367.06    46.9 2355.84      60    2345    93.4 2343.65
   106.4 2333.03     125 2320.02   148.2 2318.97   156.4 2316.93   165.7 2310.64
   213.1  2310.7   235.1 2308.07   244.4 2308.49   258.3 2311.94   333.8    2312
   350.9 2310.01  366.152312.197   382.6 2312.91   388.3  2308.6   394.2 2307.09
  406.342308.542  410.782310.345   419.8 2313.79   442.2 2332.27   449.1 2336.58
   494.7 2356.69   512.9 2366.95   525.1 2370.01   554.8 2386.33602.7344 2416.28
#Mann= 5 ,-1 , 0
       0      .1       0  366.15     .06       0   388.3    .045       0
  406.34     .06       0  410.78      .1       0
#XS Ineff= 2 , 0
          372.12  2312.7
Permanent Ineff=
       F       F
Bank Sta=388.3,406.34
XS Rating Curve= 0 ,0
Exp/Cntr(USF)=0,0
Exp/Cntr=0.3,0.1

Type RM Length L Ch R = 1 ,11860   ,328.5,328.5,328.5
XS GIS Cut Line= 4
2165104.10406037260559.3410794122165321.47602107 260366.23389572
2165425.61235574260293.4395646952165539.85901415 260207.50181279
#Sta/Elev= 30
       0 2368.06    51.9 2339.66    69.5 2325.81    91.4 2304.94      94 2303.86
   104.6  2302.7   136.5  2303.6   152.8 2306.44   196.3 2304.55  252.662306.973
   277.6 2306.38   305.1 2307.92   309.1 2307.46   315.1 2302.98   317.1 2301.65
   321.1 2301.28   333.1 2301.88   336.12303.038     341 2306.76   345.1 2307.54
   357.1 2307.19   363.9 2309.03   369.1 2312.28  385.492325.731   411.7 2347.96
   421.1 2354.44   470.5 2374.32   505.5 2392.46   519.2 2401.66560.7761 2424.52
#Mann= 5 ,-1 , 0
       0      .1       0  252.66     .06       0   315.1    .045       0
   336.1     .06       0  385.49      .1       0
#XS Ineff= 2 , 0
           296.1 2309.14
Permanent Ineff=
       F       F
Bank Sta=315.1,336.1
XS Rating Curve= 0 ,0
Exp/Cntr(USF)=0,0
Exp/Cntr=0.3,0.1

Type RM Length L Ch R = 1 ,11532   ,136.9,136.9,136.9
XS GIS Cut Line= 4
2165201.83718999260850.9677512362165469.19908481260667.858554367
2165568.05558373 260589.222702952165689.37946877260429.704261506
#Sta/Elev= 30
       0 2374.25    55.6 2339.86    84.3 2309.02    95.6 2298.97   101.7 2296.62
   107.5 2296.56   119.1 2299.06   127.4 2298.34   159.8 2299.55   206.9 2298.36
   246.7 2299.81   262.6  2296.3   278.5 2298.64   329.3 2298.51  345.062299.533
   359.4 2301.19   376.6 2300.49   393.4 2301.56   401.8 2300.73   411.32296.076
   420.4 2294.07  425.28 2296.08   450.4 2313.28  478.442338.204   490.5 2348.47
   502.9 2356.49   539.3 2375.75   560.6  2383.2  599.952392.273650.7861 2403.14
#Mann= 6 ,-1 , 0
       0      .1       0  345.06     .06       0   411.3    .045       0
  425.28     .06       0  478.44      .1       0  599.95      .1       0
#XS Ineff= 2 , 0
          366.06  2302.7
Permanent Ineff=
       F       F
Bank Sta=411.3,425.28
XS Rating Curve= 0 ,0
Exp/Cntr(USF)=0,0
Exp/Cntr=0.3,0.1

Type RM Length L Ch R = 1 ,11395   ,292.2,292.2,292.2
XS GIS Cut Line= 4
2165210.82414444261029.583470881 2165600.6332936260731.890604806
 2165694.9963153260671.2286622842165842.15769438260554.398254466
#Sta/Elev= 30
       0 2440.11    48.4 2408.52    71.4 2394.72   129.3  2355.2   166.4 2331.89
   171.5 2327.61   199.4 2298.77   205.2 2294.67   215.9 2293.43   227.7 2296.73
   253.4 2295.29     333 2297.81     347 2297.18   356.6 2294.08   383.6 2296.05
   393.4 2293.79   405.2  2293.4  443.212296.411     508 2298.22  523.612293.187
     537 2291.43   543.1 2291.87  545.942293.186   556.7 2301.89   565.8  2306.3
   578.2 2318.52   605.7 2337.26   622.4 2343.23   697.1 2382.67790.5596 2428.18
#Mann= 5 ,-1 , 0
       0      .1       0  443.21     .06       0  523.61    .045       0
  545.94     .06       0   556.7      .1       0
#XS Ineff= 2 , 0
          471.69 2299.05
Permanent Ineff=
       F       F
Bank Sta=523.61,545.94
XS Rating Curve= 0 ,0
Exp/Cntr(USF)=0,0
Exp/Cntr=0.3,0.1

Type RM Length L Ch R = 1 ,11103   ,351.6,351.6,351.6
XS GIS Cut Line= 4
2165362.35621753261238.3760454642165721.91658066260987.254522009
2165856.98952131260905.4497833082166077.67207222260747.547613257
#Sta/Elev= 30
       0 2448.22      55 2411.55    64.5  2406.1   116.5 2370.55     176 2332.74
   228.5 2302.21   249.8 2295.17     267 2292.85   348.6 2290.97   370.2 2288.43
   399.9 2290.93   424.6 2290.59   432.6 2288.37  439.812289.245  461.672287.764
   467.4 2286.81   480.6 2286.68  490.722287.764   498.1 2288.64     514 2296.75
  546.932320.175   574.8 2340.83   592.8 2352.97   690.7 2411.95   698.7 2415.76
   743.1 2440.78   766.9 2452.92   798.1 2466.79   839.9 2481.51867.8416 2489.84
#Mann= 5 ,-1 , 0
       0      .1       0  439.81     .06       0  461.67    .045       0
  490.72     .06       0  546.93      .1       0
#XS Ineff= 2 , 0
             400 2292.79
Permanent Ineff=
       F       F
Bank Sta=461.67,490.72
XS Rating Curve= 0 ,0
Exp/Cntr(USF)=0,0
Exp/Cntr=0.3,0.1

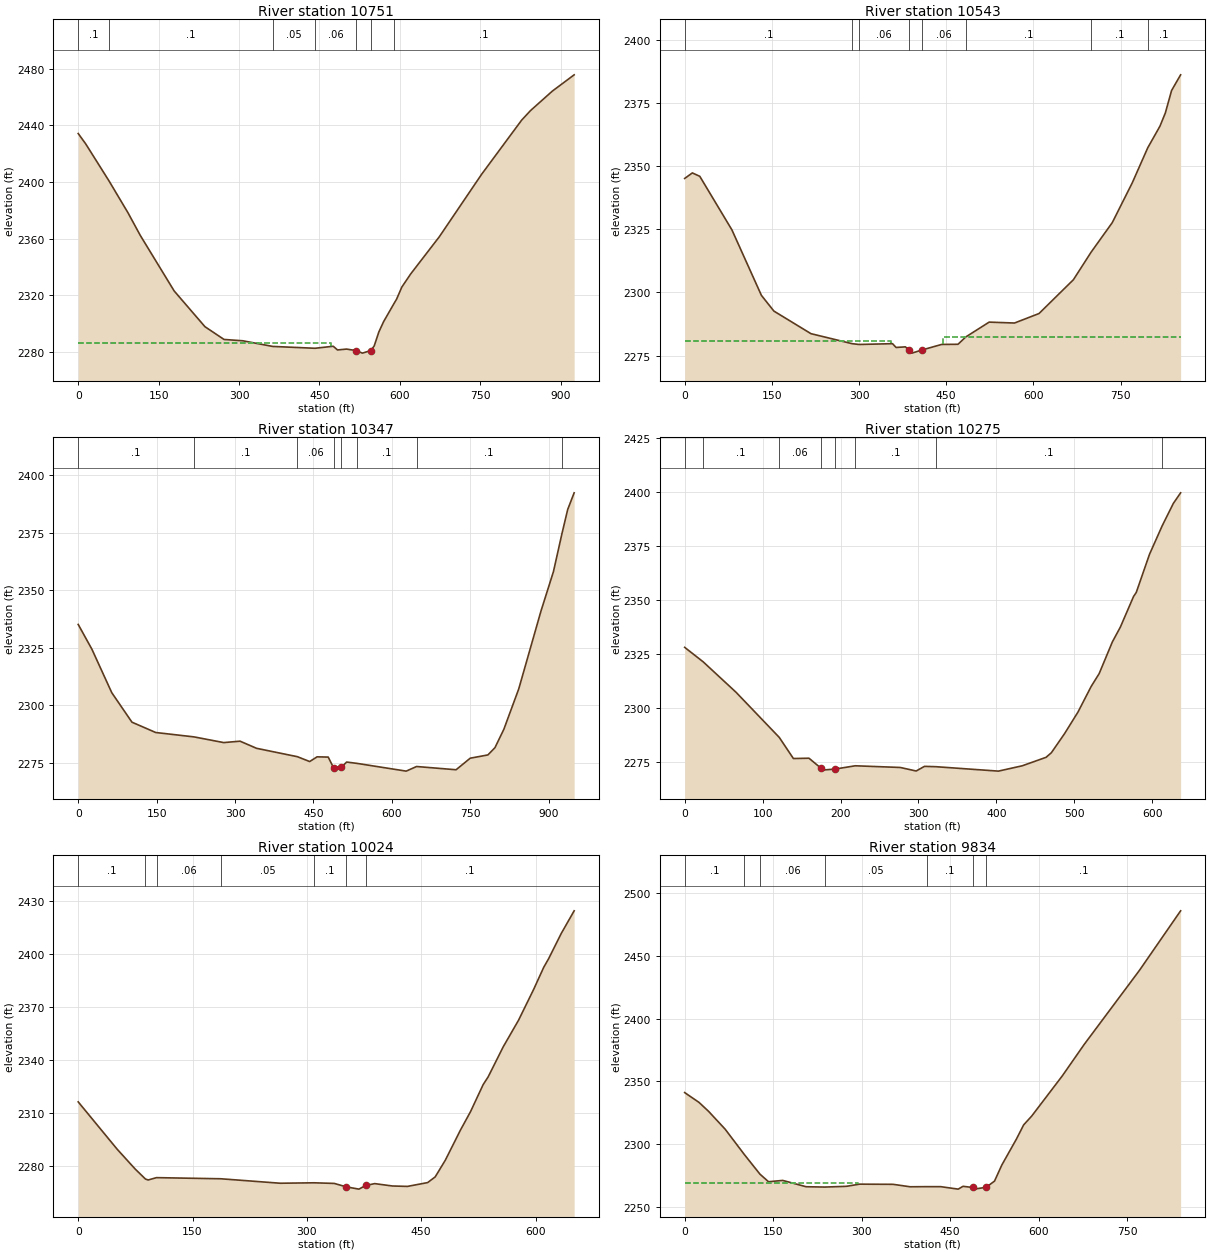
Type RM Length L Ch R = 1 ,10751   ,208.1,208.1,208.1
XS GIS Cut Line= 4
2165676.25812185261582.7169223232165993.96489774261219.351687627
2166054.84284282261150.8639994122166075.76963644260800.815815202
#Sta/Elev= 30
       0 2434.16    13.9  2426.9   57.75 2400.52      93 2378.12   115.7 2362.29
     179 2323.03   236.4 2297.81     272 2288.81   306.9 2287.88   362.82283.883
   441.72282.585   475.7 2284.01   483.6  2281.4   500.4 2282.02   518.62280.934
   530.1 2279.16   545.32280.936     552 2284.17   560.8 2294.17   569.6 2301.38
  589.012314.173   593.8 2317.24   603.6  2325.8   620.1 2335.05   673.5 2361.29
   752.2 2405.29   827.1 2443.63   843.6 2450.35   884.3  2464.1924.9782 2475.59
#Mann= 7 ,-1 , 0
       0      .1       0   57.75      .1       0   362.8     .05       0
   441.7     .06       0   518.6    .045       0   545.3     .06       0
  589.01      .1       0
#XS Ineff= 2 , 0
             471  2286.6
Permanent Ineff=
       F       F
Bank Sta=518.6,545.3
XS Rating Curve= 0 ,0
Exp/Cntr(USF)=0,0
Exp/Cntr=0.3,0.1

Type RM Length L Ch R = 1 ,10543   ,196.1,196.1,196.1
XS GIS Cut Line= 4
2165912.16015904261643.5948674032166144.25732466261362.034371408
 2166197.5255266261293.5466831932166450.54948584260981.547214658
#Sta/Elev= 30
       0 2345.11    13.2  2347.3      26 2345.96    81.3 2324.76     132 2298.86
   153.5 2292.63   217.3 2283.69  288.062279.732  299.982279.415   357.6 2279.73
   363.8 2278.23   379.8 2278.47  385.622277.289     391 2275.99  409.142277.289
   442.2 2279.43   470.3 2279.49  483.682282.387   523.9 2288.26   567.5  2287.9
   609.7 2291.66   668.9 2305.04  699.292315.927   735.8 2327.65   770.2  2343.4
  796.832357.258   817.8  2365.8   827.1 2371.05   837.8 2379.91853.3577 2386.12
#Mann= 8 ,-1 , 0
       0      .1       0  288.06     .05       0  299.98     .06       0
  385.62    .045       0  409.14     .06       0  483.68      .1       0
  699.29      .1       0  796.83      .1       0
#XS Ineff= 2 , 0
          355.29 2280.78  445.02         2282.39
Permanent Ineff=
       F       F
Bank Sta=385.62,409.14
XS Rating Curve= 0 ,0
Exp/Cntr(USF)=0,0
Exp/Cntr=0.3,0.1

Type RM Length L Ch R = 1 ,10347   ,72.1,72.1,72.1
XS GIS Cut Line= 4
2165939.08128389261643.0335870882166302.68896736261506.271237674
2166399.32344179261272.8744138242166474.66557441260974.781628275
#Sta/Elev= 30
       0 2335.16    26.2 2324.37    64.2 2305.45   102.8 2292.62   148.2 2288.13
  221.652286.215   278.3 2283.74   309.6 2284.35   341.1 2281.25  419.222277.601
   442.7 2275.49   456.9 2277.54   478.2 2277.43  488.472272.755     503 2272.92
   513.4 2275.27   533.42274.684   627.3 2271.32  647.122273.329   722.7 2271.92
   749.8 2276.95   783.6 2278.37   797.1 2281.53   814.1 2289.53   842.5 2307.05
   885.1 2340.98   908.9  2358.1  925.142374.579   936.2 2385.17948.5547 2392.43
#Mann= 8 ,-1 , 0
       0      .1       0  221.65      .1       0  419.22     .06       0
  488.47    .045       0     503     .06       0   533.4      .1       0
  647.12      .1       0  925.14      .1       0
Bank Sta=488.47,503
XS Rating Curve= 0 ,0
Exp/Cntr(USF)=0,0
Exp/Cntr=0.3,0.1

Type RM Length L Ch R = 1 ,10275   ,250.9,250.9,250.9
XS GIS Cut Line= 4
2166446.82174279261579.9754978372166417.34003872261429.291232615
2166399.32344179261328.5620770582166500.05259735260961.678648691
#Sta/Elev= 30
       0 2328.16   23.762321.456    65.9 2307.41  121.352286.566   139.5  2276.8
   159.5 2276.94  175.122272.269   179.7 2271.55   192.8 2271.93  218.912273.445
   276.6 2272.67     297 2271.04   307.7 2273.18  322.282273.028   402.5 2270.98
   433.1 2273.44   463.7 2277.36   470.5 2279.48   487.5 2288.34   504.7 2298.31
   521.6 2310.12   531.8 2316.01   548.8  2330.7     559  2337.5     576 2351.69
   579.4  2353.5   596.4 2371.13  612.542384.188     627 2394.65 636.329 2399.53
#Mann= 8 ,-1 , 0
       0      .1       0   23.76      .1       0  121.35     .06       0
  175.12    .045       0   192.8     .06       0  218.91      .1       0
  322.28      .1       0  612.54      .1       0
Bank Sta=175.12,192.8
XS Rating Curve= 0 ,0
Exp/Cntr(USF)=0,0
Exp/Cntr=0.3,0.1

Type RM Length L Ch R = 1 ,10024   ,190.1,190.1,190.1
XS GIS Cut Line= 3
2166465.29496782261567.8443484082166547.32715593261263.351989157
2166591.81919016260931.052108513
#Sta/Elev= 30
       0 2316.34      51 2289.61    74.8 2278.31    88.2 2272.69    91.8 2272.15
   102.7 2273.47     187 2272.83   265.1  2270.3   309.3 2270.55   335.9  2270.2
   351.72268.247   368.3 2266.97   377.1 2269.04     389 2270.09   412.1 2268.75
   431.9 2268.51   458.4 2270.67   468.3 2273.88   481.6 2283.35   501.4 2300.34
   514.7 2310.84   531.2 2326.08   537.8  2330.5   557.7 2347.61   577.6  2362.5
   597.4 2379.92   610.6  2392.4   617.3  2397.5   633.8 2411.73   650.6 2424.44
#Mann= 7 ,-1 , 0
       0      .1       0    88.2      .1       0   102.7     .06       0
     187     .05       0   309.3      .1       0   351.7    .045       0
   377.1      .1       0
Bank Sta=351.7,377.1
XS Rating Curve= 0 ,0
Exp/Cntr(USF)=0,0
Exp/Cntr=0.3,0.1

Type RM Length L Ch R = 1 ,9834    ,409.8,409.8,409.8
XS GIS Cut Line= 4
2166441.03730692261630.2778169172166697.86613773261268.815018004
2166779.67087643261160.3761783312166983.23150529260996.766700928
#Sta/Elev= 30
       0 2341.09    24.4 2333.23    40.5 2326.14    68.6 2311.91  101.292291.621
  127.582276.072   142.1 2270.04   166.1 2271.09   205.8 2266.06  237.432265.796
   273.9 2266.38   296.4 2268.11   353.1 2267.98   382.1 2266.02  410.462266.122
   433.8 2266.12   463.5 2264.15   471.7 2266.39   487.8 2265.49   496.3 2264.57
   511.12265.652   525.1 2270.58   537.4 2283.33   562.1 2303.99   574.4 2315.32
   588.1  2322.4   639.8 2354.33   677.1 2379.52   770.5  2438.4840.4098 2485.94
#Mann= 7 ,-1 , 0
       0      .1       0  101.29      .1       0  127.58     .06       0
  237.43     .05       0  410.46      .1       0   487.8    .045       0
   511.1      .1       0
#XS Ineff= 2 , 0
          293.76 2268.84
Permanent Ineff=
       F       F
Bank Sta=487.8,511.1
XS Rating Curve= 0 ,0
Exp/Cntr(USF)=0,0
Exp/Cntr=0.3,0.1