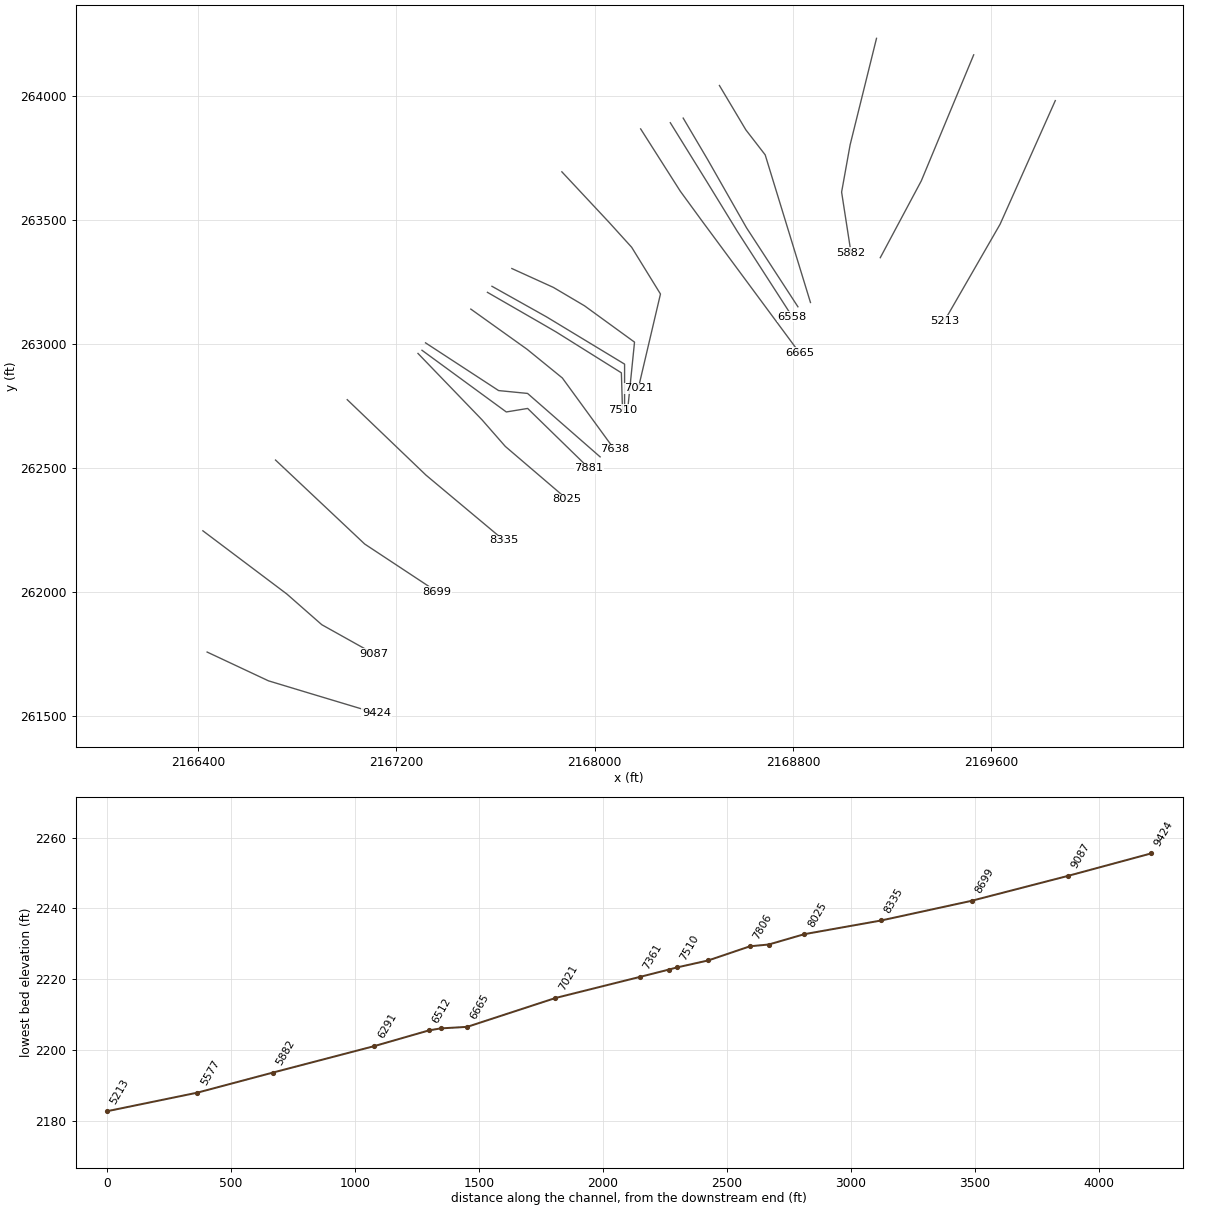
HEC-RAS study TUCKHORN.prj: TUCKHORN

--- TUCKHORN.g01 (geometry) --- (continued)

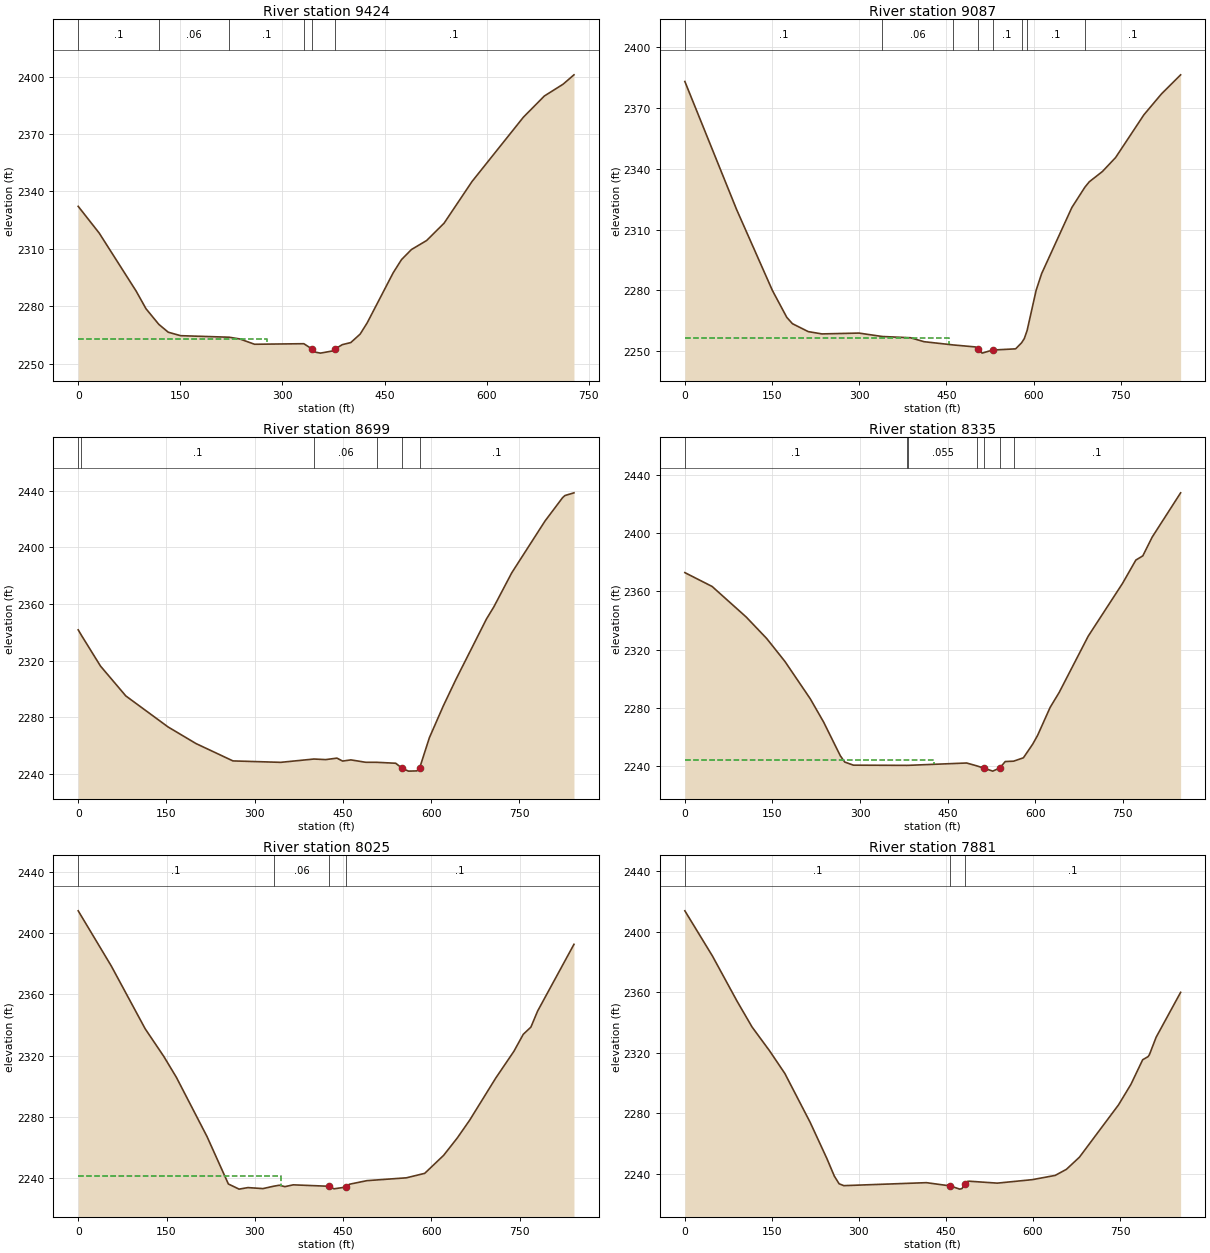
Type RM Length L Ch R = 1 ,9424    ,337,337,337
XS GIS Cut Line= 4
2166437.23243535261757.7410144282166684.54908724261641.692431619
2166848.15856464261592.2291012422167120.20688172 261510.42436254
#Sta/Elev= 30
       0 2332.19    30.8 2318.25    85.1 2287.94    99.6 2278.71   118.32270.605
   132.2 2266.46   150.4 2264.64   221.6 2263.84   237.3 2262.93   259.1 2260.16
  331.432260.449     3442257.558     349    2256   355.8 2255.53     373 2256.63
  376.492257.556     388 2259.96   400.4 2261.05   414.1 2265.46   424.4 2271.29
   462.6 2297.45   474.9 2304.38   489.5 2309.64   511.8 2314.35   537.4 2323.39
   578.5 2345.18   653.9 2378.75   684.7 2389.82   712.2 2395.98728.1946 2400.88
#Mann= 6 ,-1 , 0
       0      .1       0   118.3     .06       0   221.6      .1       0
  331.43      .1       0     344    .045       0  376.49      .1       0
#XS Ineff= 2 , 0
           276.6 2263.01
Permanent Ineff=
       F       F
Bank Sta=344,376.49
XS Rating Curve= 0 ,0
Exp/Cntr(USF)=0,0
Exp/Cntr=0.3,0.1

Type RM Length L Ch R = 1 ,9087    ,387.7,387.7,387.7
XS GIS Cut Line= 4
 2166420.1105133262246.6670108512166758.74408281261991.740615829
 2166899.5243308261868.082289885 2167110.6947028261750.131271293
#Sta/Elev= 30
       0 2382.89    89.1 2319.82   150.7 2279.98   175.4 2266.77   185.1 2263.66
   212.3 2259.75   235.8 2258.62   299.6 2259.03  339.742257.344   388.1 2256.74
   411.6 2254.79  462.262253.178   499.9 2252.21  504.092251.088   511.6 2249.16
   529.4 2250.67   569.2 2251.27  579.492254.263   584.1 2256.33  588.922260.261
   604.5 2280.11   613.9 2288.28     666 2320.88  688.312330.831   695.9 2333.51
   718.6  2338.6   741.2 2345.45     790 2366.53   820.1 2376.77853.1201 2386.18
#Mann= 8 ,-1 , 0
       0      .1       0  339.74     .06       0  462.26      .1       0
  504.09    .045       0   529.4      .1       0  579.49      .1       0
  588.92      .1       0  688.31      .1       0
#XS Ineff= 2 , 0
          453.91 2256.62
Permanent Ineff=
       F       F
Bank Sta=504.09,529.4
XS Rating Curve= 0 ,0
Exp/Cntr(USF)=0,0
Exp/Cntr=0.3,0.1

Type RM Length L Ch R = 1 ,8699    ,364.6,364.6,364.6
XS GIS Cut Line= 3
  2166713.085624262532.0323784142167072.64598713262193.398808906
2167363.71866204262001.252794748
#Sta/Elev= 30
       0 2341.85     5.22338.192    37.9 2316.28    80.9 2295.23   152.7 2273.34
   200.3 2261.59     263 2249.36   344.2 2248.35   400.62250.686   420.8 2250.28
   439.8 2251.33   449.4 2249.25   463.7 2250.08   488.6 2248.39  507.592248.377
   539.7 2247.71  550.732244.109   561.4 2242.15   575.6 2242.31  580.182244.105
   596.9  2265.7   620.6 2288.18   641.9 2306.74     694 2349.55   706.5 2358.07
   736.9 2382.07   793.5 2418.66   823.4 2435.15   827.3 2436.62842.6935 2438.54
#Mann= 6 ,-1 , 0
       0      .1       0     5.2      .1       0   400.6     .06       0
  507.59      .1       0  550.73    .045       0  580.18      .1       0
Bank Sta=550.73,580.18
XS Rating Curve= 0 ,0
Exp/Cntr(USF)=0,0
Exp/Cntr=0.3,0.1

Type RM Length L Ch R = 1 ,8335    ,309.6,309.6,309.6
XS GIS Cut Line= 3
2167002.25586313262775.5441587342167319.96263901262471.154433334
2167633.86454333262208.618295176
#Sta/Elev= 30
       0 2372.74    46.7 2363.24     105 2342.32   140.2 2327.54   171.4 2311.83
   214.8 2286.21   237.5 2270.38   266.2  2247.2   273.8 2242.83   288.7 2240.69
  380.592240.554  382.512240.567   482.7 2242.17  500.452240.165  511.632238.727
   527.4  2236.6  539.342238.725   548.8 2243.18  563.12 2243.43   579.9 2245.75
   595.8 2255.09   604.4 2261.28   625.7 2280.33   641.2 2290.59     691 2329.22
   749.8 2365.43   772.5 2381.35   784.4 2384.23   800.5 2397.12849.2078 2427.47
#Mann= 7 ,-1 , 0
       0      .1       0  380.59     .05       0  382.51    .055       0
  500.45     .06       0  511.63    .045       0  539.34     .06       0
  563.12      .1       0
#XS Ineff= 2 , 0
          425.97 2244.48
Permanent Ineff=
       F       F
Bank Sta=511.63,539.34
XS Rating Curve= 0 ,0
Exp/Cntr(USF)=0,0
Exp/Cntr=0.3,0.1

Type RM Length L Ch R = 1 ,8025    ,143.9,143.9,143.9
XS GIS Cut Line= 4
2167287.62123069262961.9828655412167546.35249728262693.739420032
2167639.57185068262587.2030161422167888.79093835262374.130208363
#Sta/Elev= 30
       0  2414.5    56.3 2378.41   113.8 2337.44   145.7 2319.23   166.8 2305.74
   218.8 2267.09   255.1 2236.09   273.3 2232.74   288.3 2233.74   313.8 2233.09
  332.192234.659   341.7 2235.28   351.1 2234.36   365.3 2235.54   425.9 2234.61
   434.6 2232.94  454.542234.078   460.7 2235.93   490.4 2238.27   557.5 2240.13
   588.6 2243.04   620.7 2254.79     644 2266.19   664.9 2277.73   709.1 2305.18
   740.1 2322.75     756 2333.85     769 2338.57   780.4 2349.04842.1377 2392.63
#Mann= 4 ,-1 , 0
       0      .1       0  332.19     .06       0   425.9    .045       0
  454.54      .1       0
#XS Ineff= 2 , 0
          344.59  2241.1
Permanent Ineff=
       F       F
Bank Sta=425.9,454.54
XS Rating Curve= 0 ,0
Exp/Cntr(USF)=0,0
Exp/Cntr=0.5,0.3

Type RM Length L Ch R = 1 ,7881    ,74.9,74.9,74.9
XS GIS Cut Line= 4
2167303.74222799262974.744572926 2167643.7296772 262726.01940146
2167729.79047797262740.2052477412167977.43212552262498.759953057
#Sta/Elev= 30
       0 2413.77    47.5 2383.92    89.7 2354.22   115.8 2336.99   146.1 2321.17
   172.3 2306.26   215.9 2273.97   244.7 2250.06   257.6  2238.4   265.8 2233.35
   273.9 2232.12   416.2 2234.09   457.42231.946   473.6 2229.82   477.5 2230.16
   482.82233.146   486.9 2234.92   490.2 2235.05   538.4 2233.78   598.7 2236.08
   638.1 2238.88   657.5 2242.91   679.9 2250.92   747.2 2285.47   768.7  2299.1
   788.9 2315.34   798.2 2317.39   800.5 2318.69   812.1 2330.23   854.3 2359.89
#Mann= 3 , 0 , 0
       0      .1       0   457.4    .045       0   482.8      .1       0
Bank Sta=457.4,482.8
XS Rating Curve= 0 ,0
Exp/Cntr(USF)=0,0
Exp/Cntr=0.5,0.3

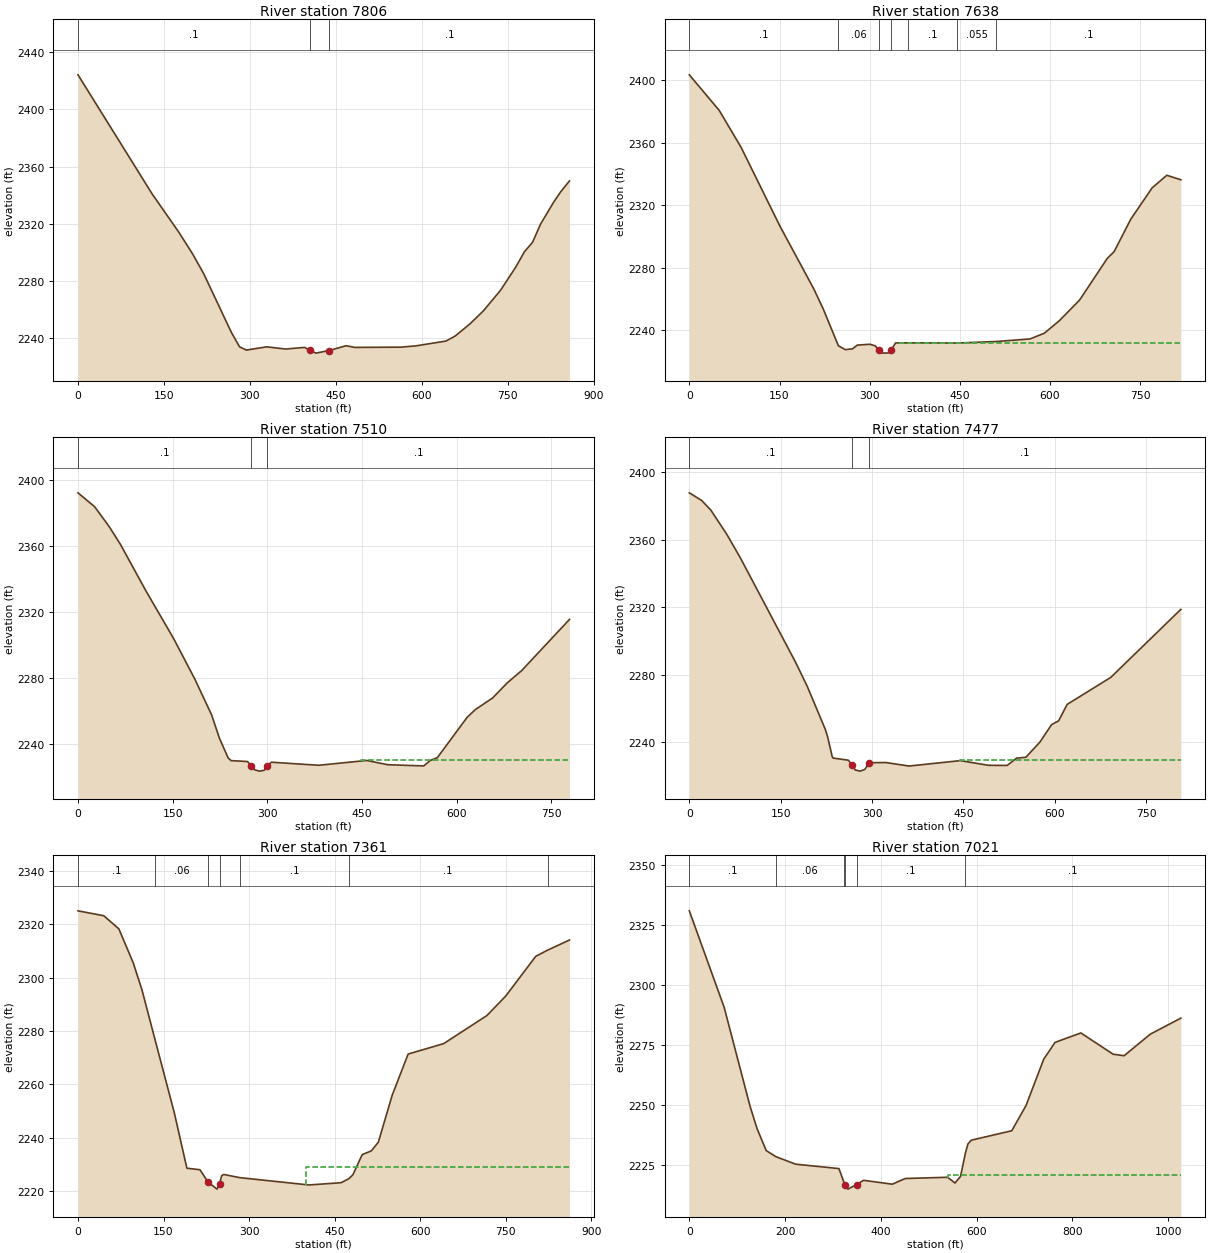
Type RM Length L Ch R = 1 ,7806    ,168.7,168.7,168.7
XS GIS Cut Line= 4
2167317.97729915263004.7023444362167612.75000296262812.271263954
2167729.50593943262800.7398134382168022.11649627 262544.88575512
#Sta/Elev= 30
       0  2424.2   129.4 2340.82   175.5 2314.32     200 2298.87   219.6 2284.82
   267.9 2243.74   282.1 2233.73     294 2231.47   329.3 2233.74   362.5 2232.19
   395.5 2233.35   405.4  2231.2   415.3 2229.33   438.4 2231.16     468 2234.52
   483.4 2233.35   563.1  2233.5   589.6  2234.4   642.4 2237.78   658.6 2241.33
   684.2  2249.8   707.7 2258.94   737.6 2273.34     764 2289.45   779.5 2300.43
   793.5 2306.92   807.3 2319.55   829.3 2334.37   842.3 2342.13     858 2349.93
#Mann= 3 , 0 , 0
       0      .1       0   405.4    .045       0   438.4      .1       0
Bank Sta=405.4,438.4
XS Rating Curve= 0 ,0
Exp/Cntr(USF)=0,0
Exp/Cntr=0.5,0.3

Type RM Length L Ch R = 1 ,7638    ,127.2,127.2,127.2
XS GIS Cut Line= 4
2167500.69403847263140.8118292132167727.08389674262979.104787595
2167869.76658052262863.0562047862168079.03451673 262575.78840144
#Sta/Elev= 30
       0 2403.27    49.8 2380.48    86.1 2356.92   150.6 2306.61     207 2266.42
   222.8 2253.51  247.912230.069   259.4 2227.55   271.5 2228.08   279.4 2230.46
   300.4 2231.01   309.3 2229.97  315.062227.346   321.9 2225.33   331.1 2225.44
  335.782227.351   343.1 2231.85  363.45 2231.88  445.94 2231.79   510.32232.745
   566.9 2234.42   590.5 2238.06   615.6 2246.11   649.2  2259.3   695.3 2285.97
   706.5 2290.15   734.3 2310.99   769.8    2331   794.2 2339.04817.5381 2336.17
#Mann= 7 ,-1 , 0
       0      .1       0  247.91     .06       0  315.06    .045       0
  335.78     .06       0  363.45      .1       0  445.94    .055       0
   510.3      .1       0
#XS Ineff= 2 , 0
          299.22 2230.88  348.63         2232.07
Permanent Ineff=
       F       F
Bank Sta=315.06,335.78
XS Rating Curve= 0 ,0
Exp/Cntr(USF)=0,0
Exp/Cntr=0.5,0.3

Type RM Length L Ch R = 1 ,7510    ,32.8,32.8,32.8
XS GIS Cut Line= 5
2167567.66683535263208.4334007112167788.59926267263081.206796014
2167844.97512343263048.4478498942168107.80852835 262883.89128334
2168112.37954409262735.333271867
#Sta/Elev= 30
       0 2392.27    26.2 2383.91      49 2372.03    67.3 2360.96   108.1 2332.46
   151.4 2303.92   185.3 2279.09   211.8 2257.43     224 2243.47   237.9 2231.37
   242.7 2229.72   268.6 2229.17   274.72226.673     280 2224.13   287.5 2223.34
   295.1 2223.85   300.3 2226.67   306.5 2228.75   381.4  2226.9   457.5 2229.81
   490.9 2227.23     548  2226.5   557.8 2229.72   569.5 2231.54     617 2256.16
   630.2 2260.85   657.2 2267.79     680 2276.84     703 2284.32   778.9 2315.45
#Mann= 3 , 0 , 0
       0      .1       0   274.7    .045       0   300.3      .1       0
#XS Ineff= 2 , 0
                          448.11         2229.97
Permanent Ineff=
       F       F
Bank Sta=274.7,300.3
XS Rating Curve= 0 ,0
Exp/Cntr(USF)=0,0
Exp/Cntr=0.5,0.3

Type RM Length L Ch R = 1 ,7477    ,116.9,116.9,116.9
XS GIS Cut Line= 4
 2167585.9508983263232.8121513122167806.12148967263109.394726396
 2168120.7597396262918.935737328 2168120.7597396262732.285928042
#Sta/Elev= 30
       0 2387.75    20.2 2383.23    35.2 2377.55    61.5 2363.17    83.9 2349.11
   174.4 2287.29   193.2 2273.31   223.3 2247.41     227 2243.13   234.5 2231.36
   235.9 2230.48     261 2229.21   267.1 2226.47   272.5 2223.39   280.2 2222.73
   287.9 2223.69   295.7 2227.72   322.4 2227.83   360.7 2225.75   445.1 2228.96
   491.1 2226.17   521.8 2226.12   537.2 2230.42   552.5 2230.96   575.5 2239.96
   594.7 2250.32   606.2 2252.56   620.2  2262.3   691.8 2278.31   806.8 2318.64
#Mann= 3 , 0 , 0
       0      .1       0   267.1    .045       0   295.7      .1       0
#XS Ineff= 2 , 0
                          444.32         2229.06
Permanent Ineff=
       F       F
Bank Sta=267.1,295.7
XS Rating Curve= 0 ,0
Exp/Cntr(USF)=0,0
Exp/Cntr=0.5,0.3

Type RM Length L Ch R = 1 ,7361    ,339.3,339.3,339.3
XS GIS Cut Line= 5
2167666.20595166263304.4213066162167833.62030063263228.323875266
2167959.18106235  263154.12887972168160.83925543263007.641324351
2168132.30271867262726.080828356
#Sta/Elev= 30
       0 2325.12    45.2 2323.28    71.7 2318.35    96.9 2305.58   112.1 2295.53
  134.292277.443   168.9 2249.32     191 2228.51   213.9 2227.94  228.112223.316
   243.8 2220.66   248.2 2222.73     252 2225.69   255.8 2226.16  283.922224.963
   405.2 2222.22   461.6 2223.08  475.182224.601   482.2 2226.09   498.4  2233.6
   514.6 2235.04   526.8 2238.32   551.1 2255.95     579 2271.36   641.4 2275.28
   717.1 2285.81   750.1 2293.12   802.8 2308.05  823.452310.351861.9926 2314.17
#Mann= 7 ,-1 , 0
       0      .1       0  134.29     .06       0  228.11    .045       0
   248.2     .06       0  283.92      .1       0  475.18      .1       0
  823.45      .1       0
#XS Ineff= 2 , 0
                          399.05         2229.04
Permanent Ineff=
       F       F
Bank Sta=228.11,248.2
XS Rating Curve= 0 ,0
Exp/Cntr(USF)=0,0
Exp/Cntr=0.3,0.1

Type RM Length L Ch R = 1 ,7021    ,356,356,356
XS GIS Cut Line= 5
2167867.86414473263694.4206422842168058.10772311263490.860013423
2168149.42464073263390.0309168852168265.47322354263201.689774293
 2168176.0587417262821.202617544
#Sta/Elev= 30
       0 2330.88    72.8 2290.58   126.8 2249.36   141.4 2240.03   160.6 2230.82
  180.722228.285     222 2225.15   312.5  2223.3  323.542217.317  324.942216.588
   331.1 2214.73  349.232216.589   363.9 2218.41     424 2216.79     451 2219.16
   539.6 2219.68     555 2217.27   566.6 2220.08  576.782229.847     582 2233.57
   588.8 2235.15   673.5 2239.09   703.4 2249.64   740.4    2269     764 2275.97
   817.9 2279.91   885.3 2271.04   908.2  2270.4     963 2279.41 1026.73  2286.1
#Mann= 6 ,-1 , 0
       0      .1       0  180.72     .06       0  323.54      .1       0
  324.94    .045       0  349.23      .1       0  576.78      .1       0
#XS Ineff= 2 , 0
                          540.58         2220.75
Permanent Ineff=
       F       F
Bank Sta=324.94,349.23
XS Rating Curve= 0 ,0
Exp/Cntr(USF)=0,0
Exp/Cntr=0.3,0.1

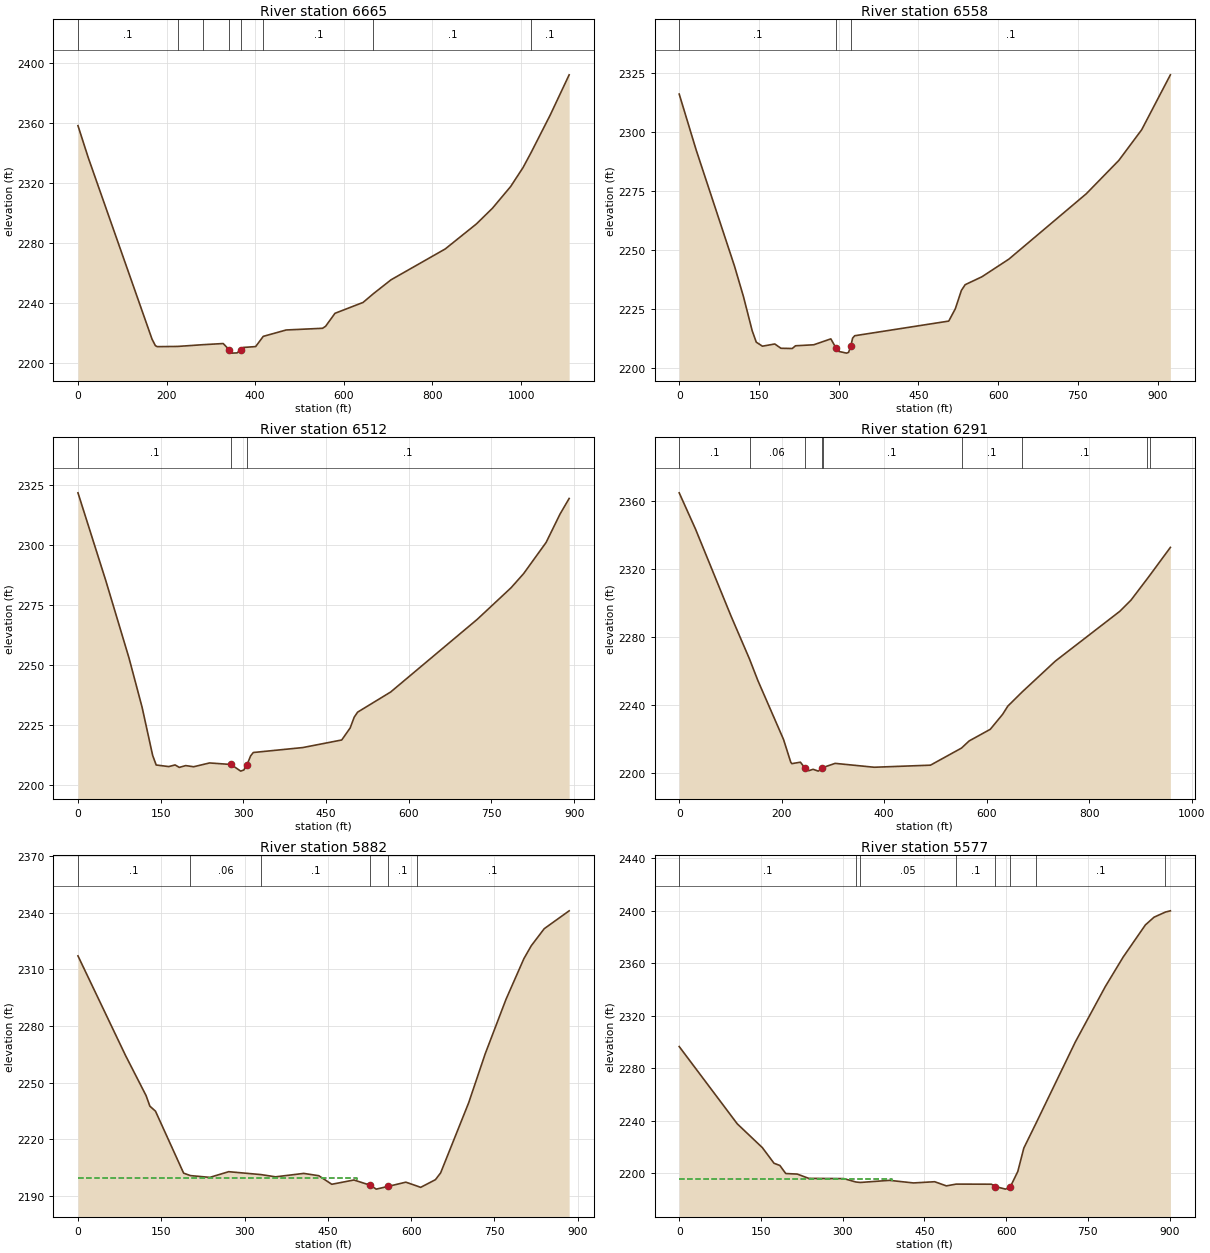
Type RM Length L Ch R = 1 ,6665    ,107.4,107.4,107.4
XS GIS Cut Line= 4
2168185.57092062263867.5422986062168345.37552645263616.420775151
2168432.88757251263496.5673207752168826.69177974262963.885301325
#Sta/Elev= 30
       0 2358.33    23.2 2336.99   167.1 2215.95   174.7 2211.58   178.8 2210.91
  225.072211.058  281.292212.201   327.8 2212.99  340.752208.969   348.2 2206.59
   359.4 2206.76  366.812208.969   372.5 2210.36     401 2210.96  418.16 2217.77
   469.8 2222.03   551.9 2223.16   558.9 2224.51     580 2233.15   643.4 2240.41
  666.532246.199   706.6 2255.52   828.7 2276.06   899.1 2292.75   935.3 2303.22
   976.5 2317.74  1004.6 2330.47 1023.112340.687  1065.8 2365.451108.503 2392.25
#Mann= 8 ,-1 , 0
       0      .1       0  225.07     .06       0  281.29    .055       0
  340.75    .045       0  366.81    .055       0  418.16      .1       0
  666.53      .1       0 1023.11      .1       0
Bank Sta=340.75,366.81
XS Rating Curve= 0 ,0
Exp/Cntr(USF)=0,0
Exp/Cntr=0.5,0.3

Type RM Length L Ch R = 1 ,6558    ,46.4,46.4,46.4
XS GIS Cut Line= 4
2168305.16921254263892.4910036332168454.36988444263651.735373985
2168575.31285332263454.496606973 2168797.1701481263110.280572518
#Sta/Elev= 30
       0 2316.04      32 2292.28   104.2 2242.94   120.9 2230.13   137.3 2215.67
     145  2210.8   156.6 2209.09   179.8 2210.03   191.4 2208.21   212.6 2208.11
   218.9 2209.27   253.1 2209.69   285.3  2212.2   295.32208.223     300 2206.89
   314.8 2206.15   318.7 2206.48   322.82209.169   326.3 2212.53   330.2 2213.53
   507.1 2219.74   519.5 2224.98   530.9 2232.75     538 2235.18   569.6 2238.55
   620.3 2246.03   765.9 2273.76   827.2 2287.93   870.1 2300.92   924.1 2324.21
#Mann= 3 , 0 , 0
       0      .1       0   295.3    .045       0   322.8      .1       0
Bank Sta=295.3,322.8
XS Rating Curve= 0 ,0
Exp/Cntr(USF)=0,0
Exp/Cntr=0.5,0.3

Type RM Length L Ch R = 1 ,6512    ,220.7,220.7,220.7
XS GIS Cut Line= 4
2168357.14805344263911.0837194432168455.52672318 263744.32838563
2168612.51396213263468.7285661472168819.85579712263150.166739763
#Sta/Elev= 30
       0 2321.93    50.5  2285.2    92.4 2253.02   116.3  2232.3   135.5 2212.13
   141.9 2208.16   164.7  2207.5   176.2 2208.19   183.8 2207.16   195.4 2207.91
   209.8 2207.43   238.7 2209.02   277.62208.374   295.1  2205.6   300.9 2206.08
   306.52208.222   313.2 2211.99     318 2213.38   407.8 2215.45   478.4 2218.62
   493.7 2223.65     501 2228.13   507.2 2230.25   567.2 2238.68   724.1 2269.03
   785.6 2282.26   808.3 2288.15   849.1 2301.19   874.4 2313.07   890.9 2319.57
#Mann= 3 , 0 , 0
       0      .1       0   277.6    .045       0   306.5      .1       0
Bank Sta=277.6,306.5
XS Rating Curve= 0 ,0
Exp/Cntr(USF)=0,0
Exp/Cntr=0.5,0.3

Type RM Length L Ch R = 1 ,6291    ,409.1,409.1,409.1
XS GIS Cut Line= 4
2168503.27769651 264042.56639071 2168609.8141004263863.737427038
2168687.81396753263762.9083304992168870.44780277263167.445930186
#Sta/Elev= 30
       0 2364.78    31.8 2343.49     101 2292.43  137.332266.973   153.3 2254.58
   203.6 2219.77   217.7 2206.38   219.8 2205.57   236.5 2206.41   245.42202.979
   252.6 2201.41   261.3 2202.23   271.5 2201.16  279.392202.979  280.332203.253
   304.3 2205.72   380.5 2203.44   490.3 2204.66  550.92 2214.72   565.8 2218.91
     607 2225.74     631 2234.51   641.3 2239.39  669.312247.735     734 2265.85
   859.8 2295.12   881.6 2301.69  913.182314.208   919.32316.676958.4763  2332.7
#Mann= 9 ,-1 , 0
       0      .1       0  137.33     .06       0   245.4    .045       0
  279.39     .06       0  280.33      .1       0  550.92      .1       0
  669.31      .1       0  913.18      .1       0   919.3      .1       0
Bank Sta=245.4,279.39
XS Rating Curve= 0 ,0
Exp/Cntr(USF)=0,0
Exp/Cntr=0.3,0.1

Type RM Length L Ch R = 1 ,5882    ,304.9,304.9,304.9
XS GIS Cut Line= 4
2169136.78881249264232.809969085 2169030.2524086263802.859481958
 2168996.0085645263612.6159035832169034.05728017 263367.20168748
#Sta/Elev= 30
       0 2317.13    85.7  2264.4   122.7 2243.16   129.5 2237.59   139.6 2234.95
   190.3 2202.14  202.652200.845   237.6 2199.91   271.4 2202.92  329.782201.376
   355.9  2200.2   406.6 2202.01   433.7 2200.79   457.1 2196.26     497 2198.52
  525.982195.795   537.2 2193.69   559.1 2195.17   590.5 2197.37  610.452195.344
   617.2 2194.63   643.8 2198.69   653.1 2202.27   703.6 2239.35   733.4  2265.3
   770.9 2294.17   803.2 2315.73   816.4 2322.51   839.7 2331.52884.6002 2340.98
#Mann= 6 ,-1 , 0
       0      .1       0  202.65     .06       0  329.78      .1       0
  525.98    .045       0   559.1      .1       0  610.45      .1       0
#XS Ineff= 2 , 0
          503.03 2199.46
Permanent Ineff=
       F       F
Bank Sta=525.98,559.1
XS Rating Curve= 0 ,0
Exp/Cntr(USF)=0,0
Exp/Cntr=0.3,0.1

Type RM Length L Ch R = 1 ,5577    ,364.3,364.3,364.3
XS GIS Cut Line= 3
2169528.69058395264166.2247166542169317.52021195263658.274362393
2169152.00829876263348.177329642
#Sta/Elev= 30
       0 2296.52   106.6  2237.7   152.6 2219.62   174.1 2207.69   184.8 2206.02
   195.5  2199.9   216.8 2199.46   237.9  2196.2   302.1 2196.03  324.472193.438
  332.51 2193.09     386  2194.7     430 2192.73     469 2193.65   490.4 2190.49
   508.42191.838   573.1 2191.77  580.232189.985   599.1 2188.02  608.042189.985
   621.5 2201.43   632.6 2219.28   655.32238.445   727.2 2300.08   781.9 2341.98
   814.8 2364.55   855.7 2389.08   871.6 2394.97   892.62398.905901.5998 2399.82
#Mann= 8 ,-1 , 0
       0      .1       0  324.47     .06       0  332.51     .05       0
   508.4      .1       0  580.23    .045       0  608.04      .1       0
   655.3      .1       0   892.6      .1       0
#XS Ineff= 2 , 0
          391.34 2195.61
Permanent Ineff=
       F       F
Bank Sta=580.23,608.04
XS Rating Curve= 0 ,0
Exp/Cntr(USF)=0,0
Exp/Cntr=0.3,0.1

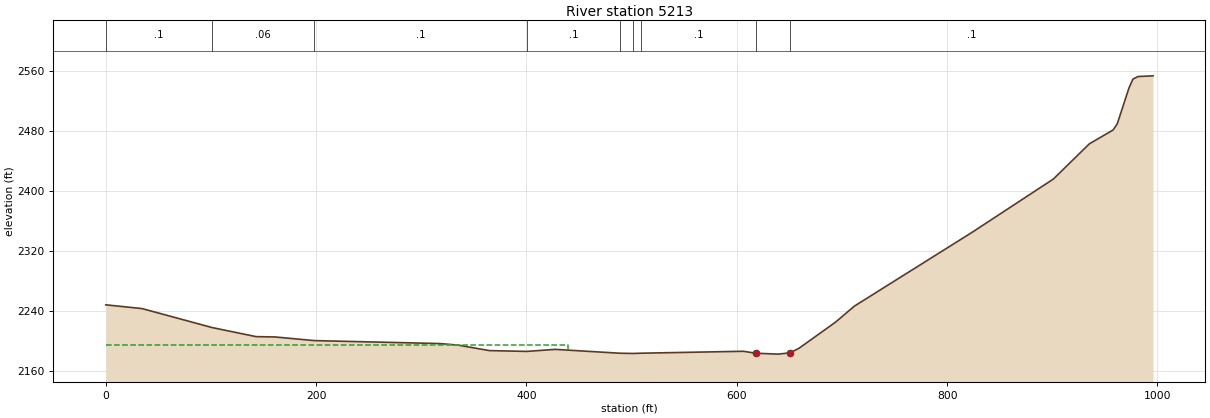
Type RM Length L Ch R = 1 ,5213    ,413.6,413.6,413.6
XS GIS Cut Line= 3
2169857.81197454 263981.688445632169635.22698784263483.250270288
2169410.73956535 263093.25093462
#Sta/Elev= 30
       0 2248.37    34.5 2243.37   101.22218.093   142.9 2206.06   161.1 2205.59
  198.282200.771   317.6 2196.84     335 2194.76   364.8 2187.47   400.42186.388
   427.3 2189.11  488.812183.979  501.462183.653  508.692183.993   606.2 2186.57
   618.2 2183.96   639.7 2182.78  651.03 2184.67   659.4 2190.76   693.8 2225.16
   711.8 2246.57   823.8  2344.8   901.1  2415.7   935.3 2462.52   957.9 2480.96
   961.8 2488.99     973 2536.87   976.8  2548.7   981.7 2552.07995.8732 2552.99
#Mann= 9 ,-1 , 0
       0      .1       0   101.2     .06       0  198.28      .1       0
   400.4      .1       0  488.81     .05       0  501.46      .1       0
  508.69      .1       0   618.2    .045       0  651.03      .1       0
#XS Ineff= 2 , 0
          439.83 2194.59
Permanent Ineff=
       F       F
Bank Sta=618.2,651.03
XS Rating Curve= 0 ,0
Exp/Cntr(USF)=0,0
Exp/Cntr=0.3,0.1