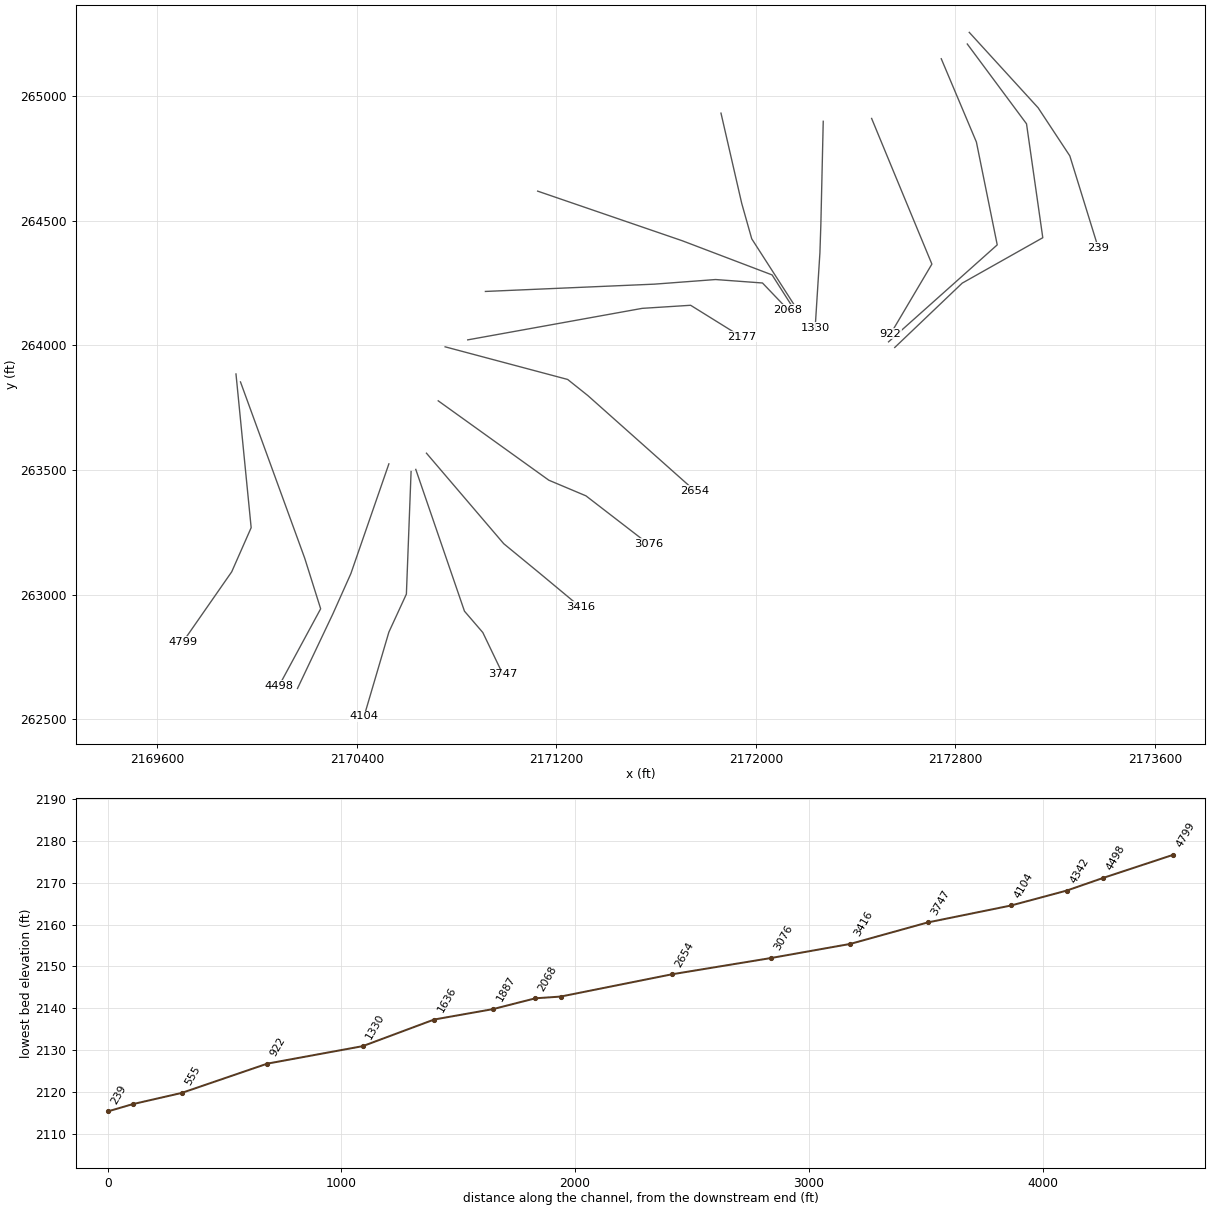
HEC-RAS study TUCKHORN.prj: TUCKHORN

--- TUCKHORN.g01 (geometry) --- (continued)

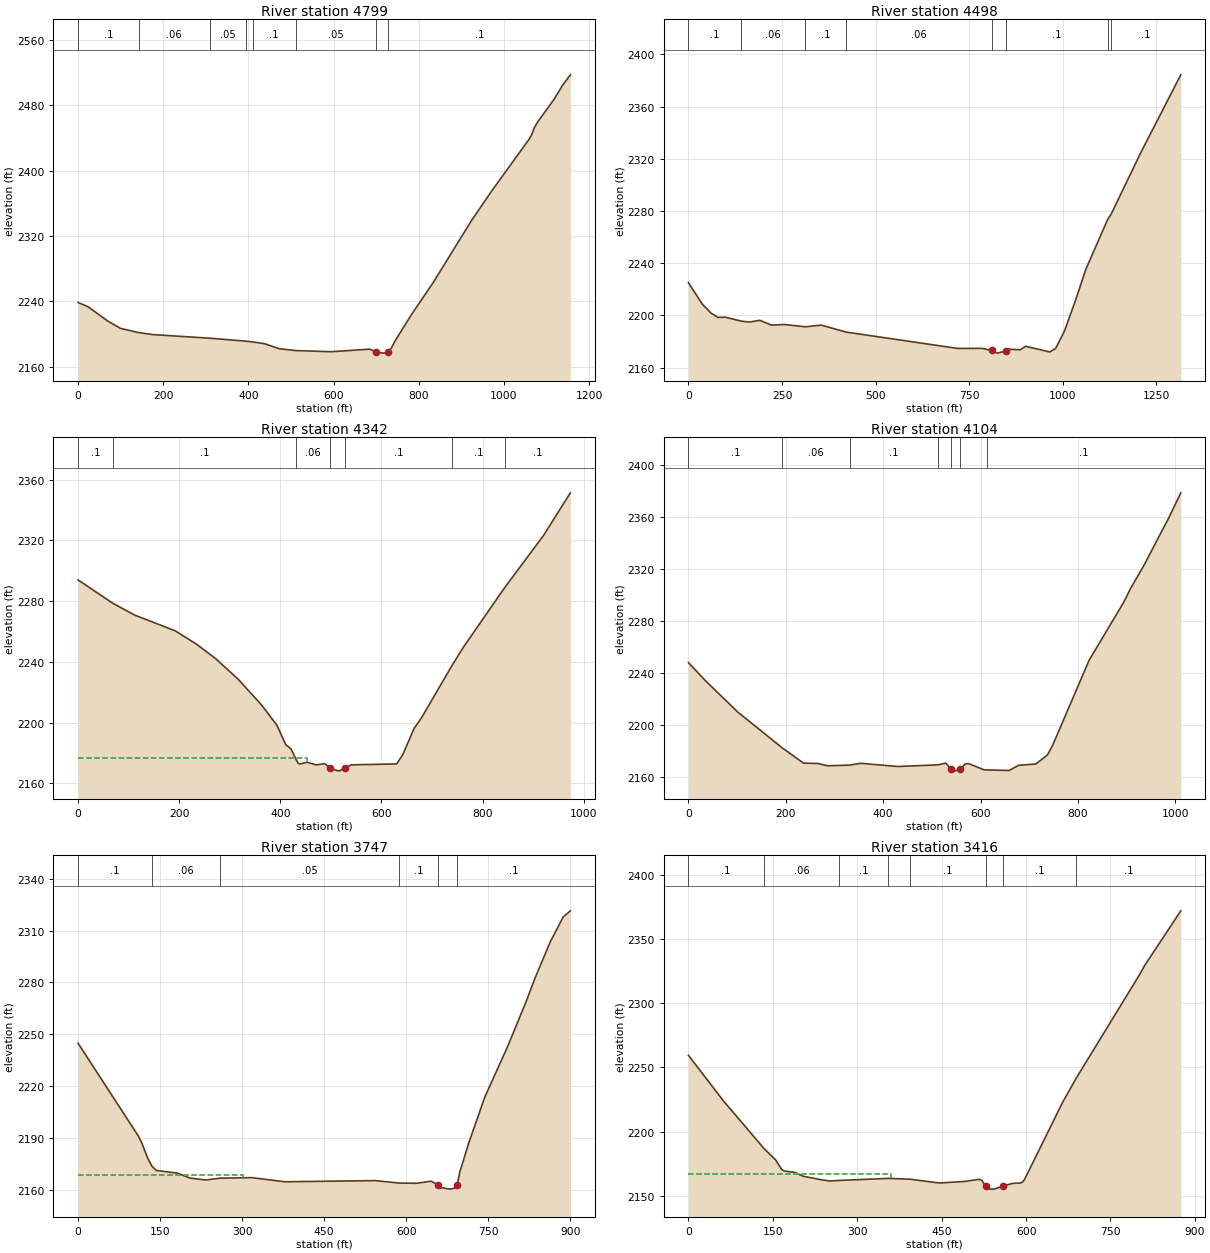
Type RM Length L Ch R = 1 ,4799    ,300.5,300.5,300.5
XS GIS Cut Line= 4
2169914.88504805263884.6642206592169975.76299313263268.275026725
2169897.76312599263091.3484988362169701.81224027262809.788002841
#Sta/Elev= 30
       0 2238.72    23.7 2233.36    69.9 2215.89    99.5 2206.96  142.642201.725
   175.4 2199.32  309.13 2194.89  393.352191.275  409.852190.358   437.9 2188.15
   472.1 2182.05  510.572179.773   594.1 2178.33   685.1  2181.5     700 2177.81
   717.3 2176.62  728.322178.309   735.3  2182.7   744.7 2191.97   782.5 2223.58
   834.3 2263.44   922.7 2338.14   970.2 2374.49  1058.1 2437.94  1064.2 2443.17
  1071.2 2452.47  1078.1  2458.9  1118.4 2488.08  1137.2 2504.34 1155.78 2517.35
#Mann= 8 ,-1 , 0
       0      .1       0  142.64     .06       0  309.13     .05       0
  393.35     .06       0  409.85      .1       0  510.57     .05       0
     700    .045       0  728.32      .1       0
Bank Sta=700,728.32
XS Rating Curve= 0 ,0
Exp/Cntr(USF)=0,0
Exp/Cntr=0.3,0.1

Type RM Length L Ch R = 1 ,4498    ,156.1,156.1,156.1
XS GIS Cut Line= 4
2169932.93916364263852.7603725662170190.60981771263145.564799629
2170254.40609928262943.0809494222170087.98101692262635.194547051
#Sta/Elev= 30
       0 2225.08      37 2208.67      60 2201.86    78.5 2198.48    99.4 2198.59
  140.722195.642   162.3  2194.9   190.2 2196.24   221.6 2192.58   256.5 2193.05
  312.34 2191.28   354.5 2192.57  420.312187.268   718.7  2174.7   783.3 2174.77
  809.462173.264   824.6  2171.1   847.8 2172.67   855.7  2174.1   886.5 2173.67
   900.3 2176.34     965    2172   980.6 2174.63  1004.2 2188.02  1033.9 2211.65
  1061.5 2235.47 1119.842273.695 1128.412277.292  1207.5 2324.431314.959 2384.39
#Mann= 8 ,-1 , 0
       0      .1       0  140.72     .06       0  312.34      .1       0
  420.31     .06       0  809.46    .045       0   847.8      .1       0
 1119.84      .1       0 1128.41      .1       0
Bank Sta=809.46,847.8
XS Rating Curve= 0 ,0
Exp/Cntr(USF)=0,0
Exp/Cntr=0.3,0.1

Type RM Length L Ch R = 1 ,4342    ,238,238,238
XS GIS Cut Line= 4
2170527.98016986263524.2161058482170375.59506358263084.182709066
2170303.68299095262923.2366417612170161.57103791262623.603005821
#Sta/Elev= 30
       0 2294.02   69.172278.545   112.2 2270.82   192.1 2260.49   233.8 2251.79
     272 2242.22   317.1 2228.47   362.9 2211.69   393.5 2198.18   410.8 2185.49
   421.2 2182.73  430.232176.436   435.1 2173.31   438.6 2172.78   452.5 2173.95
     471  2172.2     488 2173.01  497.742170.225   515.7 2168.08  528.692170.223
   540.5 2172.22   629.9 2172.81     642 2178.83   664.5 2196.18   679.3 2203.22
  739.632237.675   762.3 2249.81   843.6 2288.86   920.7 2323.39973.5797 2351.36
#Mann= 7 ,-1 , 0
       0      .1       0   69.17      .1       0  430.23     .06       0
  497.74    .045       0  528.69      .1       0  739.63      .1       0
   843.6      .1       0
#XS Ineff= 2 , 0
          453.68 2176.46
Permanent Ineff=
       F       F
Bank Sta=497.74,528.69
XS Rating Curve= 0 ,0
Exp/Cntr(USF)=0,0
Exp/Cntr=0.3,0.1

Type RM Length L Ch R = 1 ,4104    ,357.6,357.6,357.6
XS GIS Cut Line= 4
2170617.01416454263493.3966461512170598.18005028263001.997483208
2170527.98016986 262849.612376932170428.67302195262512.310512471
#Sta/Elev= 30
       0 2248.08    35.9 2233.76   101.6 2209.91   192.92182.354   236.2 2170.69
   265.7 2170.44   285.4 2168.66  330.832169.157   354.4 2170.55   429.9 2168.09
  512.442169.364   528.7 2170.67  538.572166.448   546.5 2164.53   558.3 2166.22
   568.2 2169.94   574.7  2170.4   607.6 2165.46  613.832165.464   658.5 2165.03
   678.2 2169.03   713.3 2170.02   737.2 2176.91   747.5 2184.02   822.7 2249.76
   894.5 2294.94   907.8 2304.99   935.6 2323.06   986.9 2359.891011.154 2378.81
#Mann= 7 ,-1 , 0
       0      .1       0   192.9     .06       0  330.83      .1       0
  512.44      .1       0  538.57    .045       0   558.3      .1       0
  613.83      .1       0
#XS Ineff= 2 , 0
          364.68 2169.71
Permanent Ineff=
       F       F
Bank Sta=538.57,558.3
XS Rating Curve= 0 ,0
Exp/Cntr(USF)=0,0
Exp/Cntr=0.3,0.1

Type RM Length L Ch R = 1 ,3747    ,330.3,330.3,330.3
XS GIS Cut Line= 4
 2170635.8482788263501.9576071782170831.03819021262933.509794994
2170904.66245504262847.9001847252170985.13548869262680.105348598
#Sta/Elev= 30
       0 2244.89   109.9 2191.36   116.4 2187.31   127.3 2178.46  134.942173.792
   142.8 2171.33   182.3 2169.66   204.7 2166.88   233.1 2165.77  259.612166.808
   317.5 2167.13   377.8 2164.73     543 2165.41  587.532163.982   618.6 2163.86
   645.5 2165.08  658.362162.961   662.8 2161.41   680.1 2160.48   688.8 2161.07
   693.12162.964   697.9 2170.29   713.9 2186.84   743.7 2213.77   785.3 2242.89
   819.7 2269.34   835.4  2282.5   863.9 2303.89     887 2317.88900.0338 2321.41
#Mann= 6 ,-1 , 0
       0      .1       0  134.94     .06       0  259.61     .05       0
  587.53      .1       0  658.36    .045       0   693.1      .1       0
#XS Ineff= 2 , 0
          302.16 2168.92
Permanent Ineff=
       F       F
Bank Sta=658.36,693.1
XS Rating Curve= 0 ,0
Exp/Cntr(USF)=0,0
Exp/Cntr=0.3,0.1

Type RM Length L Ch R = 1 ,3416    ,340.2,340.2,340.2
XS GIS Cut Line= 4
2170678.65308393263567.020910982 2170988.5598731263204.036163443
2171132.38401835263085.8949012722171295.04227786262950.631717047
#Sta/Elev= 30
       0 2259.46      62 2224.12  134.222187.003   155.1 2178.05   165.5  2170.7
   169.9 2169.54   188.7 2168.39   204.4 2165.35   235.2 2162.75   251.1  2161.7
  266.922162.128  355.412163.735  392.92 2163.12   445.9 2160.16   491.4 2161.36
   516.9 2163.04   521.5 2162.11  528.152157.808   533.5 2155.54   543.1 2155.38
  559.782157.808     576 2159.84   589.6 2160.11   593.8 2160.95   597.2 2162.88
   665.1 2223.01  688.922241.539   801.7 2322.23   810.8 2329.39874.9608 2371.87
#Mann= 8 ,-1 , 0
       0      .1       0  134.22     .06       0  266.92      .1       0
  355.41     .05       0  392.92      .1       0  528.15    .045       0
  559.78      .1       0  688.92      .1       0
#XS Ineff= 2 , 0
          359.31 2167.45
Permanent Ineff=
       F       F
Bank Sta=528.15,559.78
XS Rating Curve= 0 ,0
Exp/Cntr(USF)=0,0
Exp/Cntr=0.3,0.1

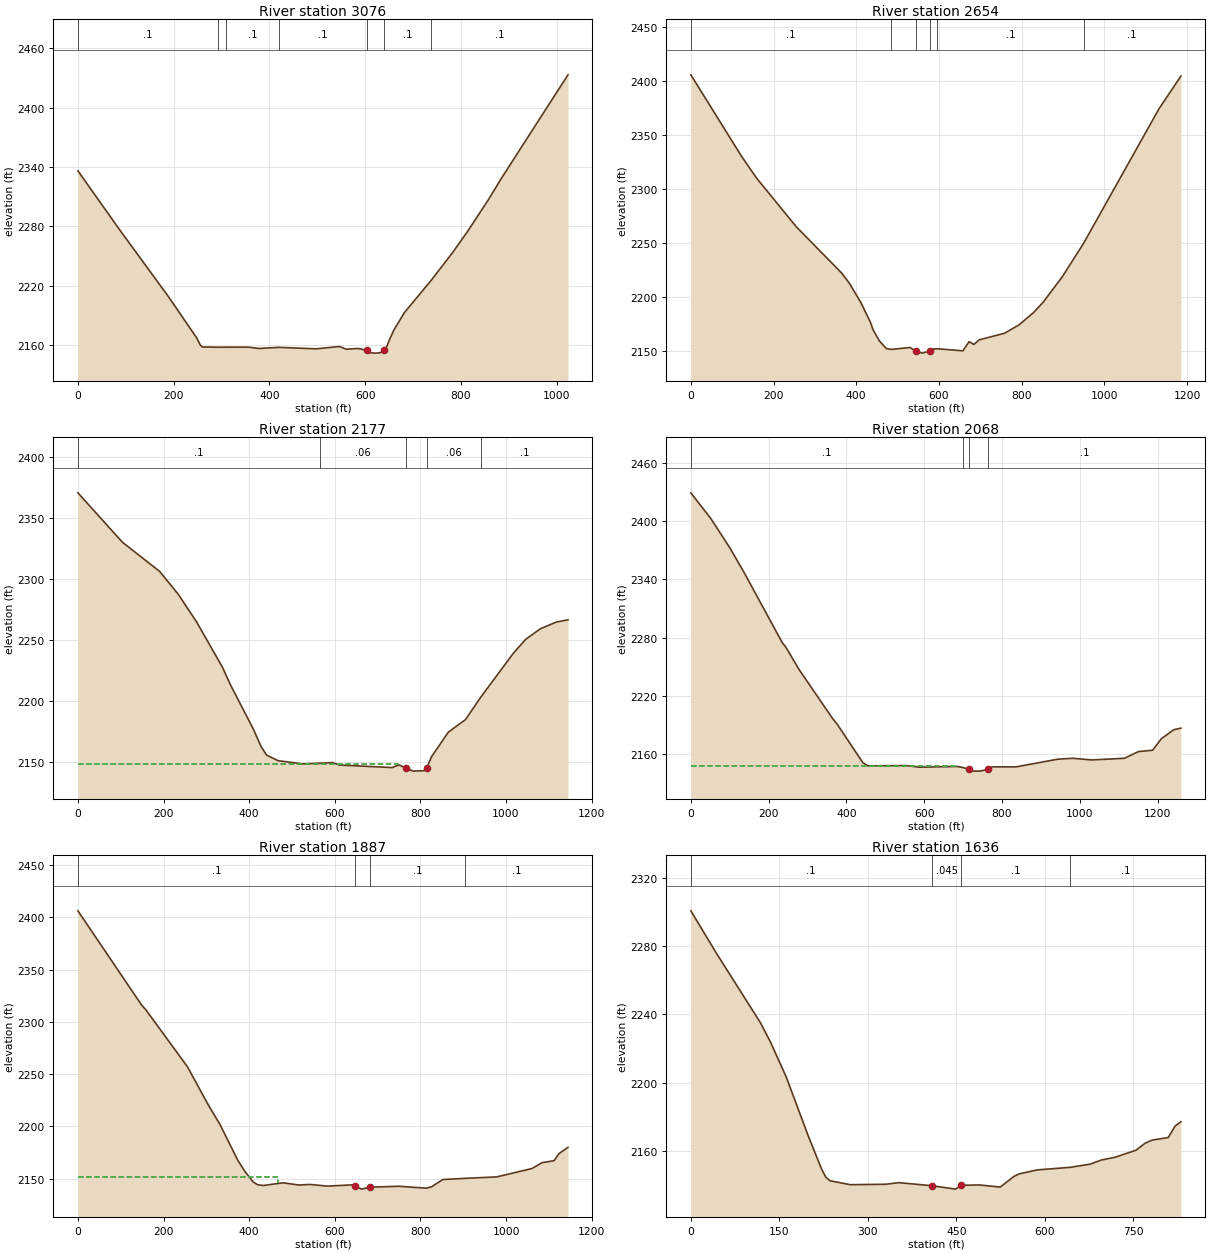
Type RM Length L Ch R = 1 ,3076    ,422.2,422.2,422.2
XS GIS Cut Line= 4
2170725.81082507  263776.97462312171169.45154281263458.597166835
2171318.20166582263395.9655360942171568.72818879 263202.85134131
#Sta/Elev= 30
       0 2336.21    85.2 2277.93   187.8 2209.97   247.7 2167.79   255.7  2160.2
   259.8 2158.26  293.062157.978  308.772157.994   356.7 2158.03   377.8 2156.73
  419.71 2157.85     498 2156.33   546.1 2158.71   560.7 2155.96   585.6 2156.74
   603.32154.889   610.5  2152.3   622.3 2152.01   631.9 2152.45  640.052154.889
   646.1  2159.6   649.8 2164.54   659.9 2175.15   681.7  2192.7  737.162225.075
   781.1  2252.5   814.2 2275.08   857.2 2306.76   885.2    23291023.775 2433.17
#Mann= 7 ,-1 , 0
       0      .1       0  293.06     .06       0  308.77      .1       0
  419.71      .1       0   603.3    .045       0  640.05      .1       0
  737.16      .1       0
Bank Sta=603.3,640.05
XS Rating Curve= 0 ,0
Exp/Cntr(USF)=0,0
Exp/Cntr=0.3,0.1

Type RM Length L Ch R = 1 ,2654    ,476.7,476.7,476.7
XS GIS Cut Line= 4
2170753.46858785263993.5237734482171244.80350118263862.665158655
2171326.03061967263797.8518333472171754.01342973263416.842746341
#Sta/Elev= 30
       0 2405.41   122.7 2330.06   159.2 2309.85   255.4 2264.81   365.4 2221.94
   383.3 2212.82   410.5 2195.47   434.2 2176.84     441 2169.59   455.9 2159.52
   472.6 2152.45  484.882151.577     530 2153.37  544.212149.949   559.4 2148.15
  577.65 2149.95   582.3 2151.77  595.522152.211     658 2150.28   673.1 2158.73
   684.7 2156.19   697.5 2160.41     759 2166.56   793.9 2174.29   828.8 2185.61
     852 2195.11   898.5 2218.77  949.922249.609  1132.4 2374.041185.386 2404.23
#Mann= 6 ,-1 , 0
       0      .1       0  484.88     .06       0  544.21    .045       0
  577.65     .06       0  595.52      .1       0  949.92      .1       0
Bank Sta=544.21,577.65
XS Rating Curve= 0 ,0
Exp/Cntr(USF)=0,0
Exp/Cntr=0.5,0.3

Type RM Length L Ch R = 1 ,2177    ,108.7,108.7,108.7
XS GIS Cut Line= 4
2170844.15052512264021.3853760932171543.75226024 264147.74516085
2171737.91485633264160.0729447282171941.32329033264033.713159972
#Sta/Elev= 30
       0 2370.99   104.2 2330.41   190.9 2306.61   234.2 2287.94   277.6 2264.97
   337.6 2228.06   356.9 2213.24   410.9 2176.57   427.6 2163.16   440.9 2155.99
   467.6 2151.39   524.3 2148.81   565.5 2149.32   594.5 2149.86     611 2147.84
     734 2145.76   750.4 2147.96  765.912145.263   783.3 2142.84   808.7 2143.18
  815.032145.264     826 2154.59   865.5 2174.83   905.5 2185.08  942.382204.059
  1017.4 2239.51    1046 2250.85  1080.4 2259.56  1117.4 2265.011144.937 2266.89
#Mann= 5 ,-1 , 0
       0      .1       0   565.5     .06       0  765.91    .045       0
  815.03     .06       0  942.38      .1       0
#XS Ineff= 2 , 0
          747.11 2148.67
Permanent Ineff=
       F       F
Bank Sta=765.91,815.03
XS Rating Curve= 0 ,0
Exp/Cntr(USF)=0,0
Exp/Cntr=0.5,0.3

Type RM Length L Ch R = 1 ,2068    ,181.1,181.1,181.1
XS GIS Cut Line= 5
2170915.03528243264215.5479721832171593.06339575264244.826458894
2171838.07810034264263.3181347122172026.07680449264249.449377849
2172127.78102149264143.122241895
#Sta/Elev= 30
       0 2429.12    51.4 2402.63   100.7  2372.2   137.3 2346.75   235.3 2274.59
   244.3 2270.11   278.9 2246.69   363.9 2196.94   376.5 2190.63   442.2 2151.15
   455.3 2147.87   553.8 2148.17   586.7 2146.48   685.6 2147.19  699.752146.124
  715.592144.174   724.8  2142.5   742.6 2142.42  764.072144.174     774 2146.85
   836.5 2146.83   942.5 2154.66   981.3 2155.67  1030.7 2153.93  1114.6 2155.65
  1150.9 2162.56  1187.2 2163.97  1209.9 2175.88  1241.7 2185.091260.018 2186.72
#Mann= 4 ,-1 , 0
       0      .1       0  699.75      .1       0  715.59    .045       0
  764.07      .1       0
#XS Ineff= 2 , 0
          681.01 2147.37
Permanent Ineff=
       F       F
Bank Sta=715.59,764.07
XS Rating Curve= 0 ,0
Exp/Cntr(USF)=0,0
Exp/Cntr=0.5,0.3

Type RM Length L Ch R = 1 ,1887    ,251.6,251.6,251.6
XS GIS Cut Line= 4
2171124.60760836264617.7419212252171704.01345066264418.956406181
2172064.60112911264281.8098105312172143.19075134264158.531971744
#Sta/Elev= 30
       0 2406.21   148.4 2316.23   158.8 2311.41   255.9 2256.91   304.4 2220.55
   332.2 2201.44   373.8 2167.13   390.6 2156.45   409.1 2146.79   419.4 2144.12
   432.8  2143.3   478.8 2145.92     516 2143.77   542.2 2144.32   582.7 2142.75
   641.1 2143.93  648.062142.665   662.3 2139.85   681.2 2141.68     750  2142.6
     814 2140.74   826.7 2142.22   852.1 2149.02  904.09 2150.16   978.2 2151.56
    1061 2159.63    1084  2165.2  1112.1 2167.08  1123.8 2173.971144.544 2179.83
#Mann= 4 ,-1 , 0
       0      .1       0  648.06    .045       0   681.2      .1       0
  904.09      .1       0
#XS Ineff= 2 , 0
          467.53 2151.24
Permanent Ineff=
       F       F
Bank Sta=648.06,681.2
XS Rating Curve= 0 ,0
Exp/Cntr(USF)=0,0
Exp/Cntr=0.3,0.1

Type RM Length L Ch R = 1 ,1636    ,305.5,305.5,305.5
XS GIS Cut Line= 4
2171859.65172213264930.5594371472171942.86426331 264568.43078571
2171982.92956092264426.6612711052172151.39432135264164.563524923
#Sta/Elev= 30
       0 2300.86    43.7 2275.73   117.8 2235.19   134.6 2224.01   161.5 2203.37
     199 2168.61   222.1 2148.71   228.8 2144.36   235.6 2142.31   270.2 2139.97
   330.4 2140.23   352.3 2141.18  408.052139.389   448.6 2137.37   458.2 2139.63
   489.5 2139.81   524.3 2138.57   547.7 2144.89   556.2 2146.29   586.6 2148.65
  643.182150.185   676.4 2152.03   696.1 2154.52     718 2156.01   754.4 2160.24
   769.5 2164.26   781.7 2166.18     809  2167.7   820.7 2174.48 830.458 2176.95
#Mann= 4 ,-1 , 0
       0      .1       0  408.05    .045       0   458.2      .1       0
  643.18      .1       0
Bank Sta=408.05,458.2
XS Rating Curve= 0 ,0
Exp/Cntr(USF)=0,0
Exp/Cntr=0.3,0.1

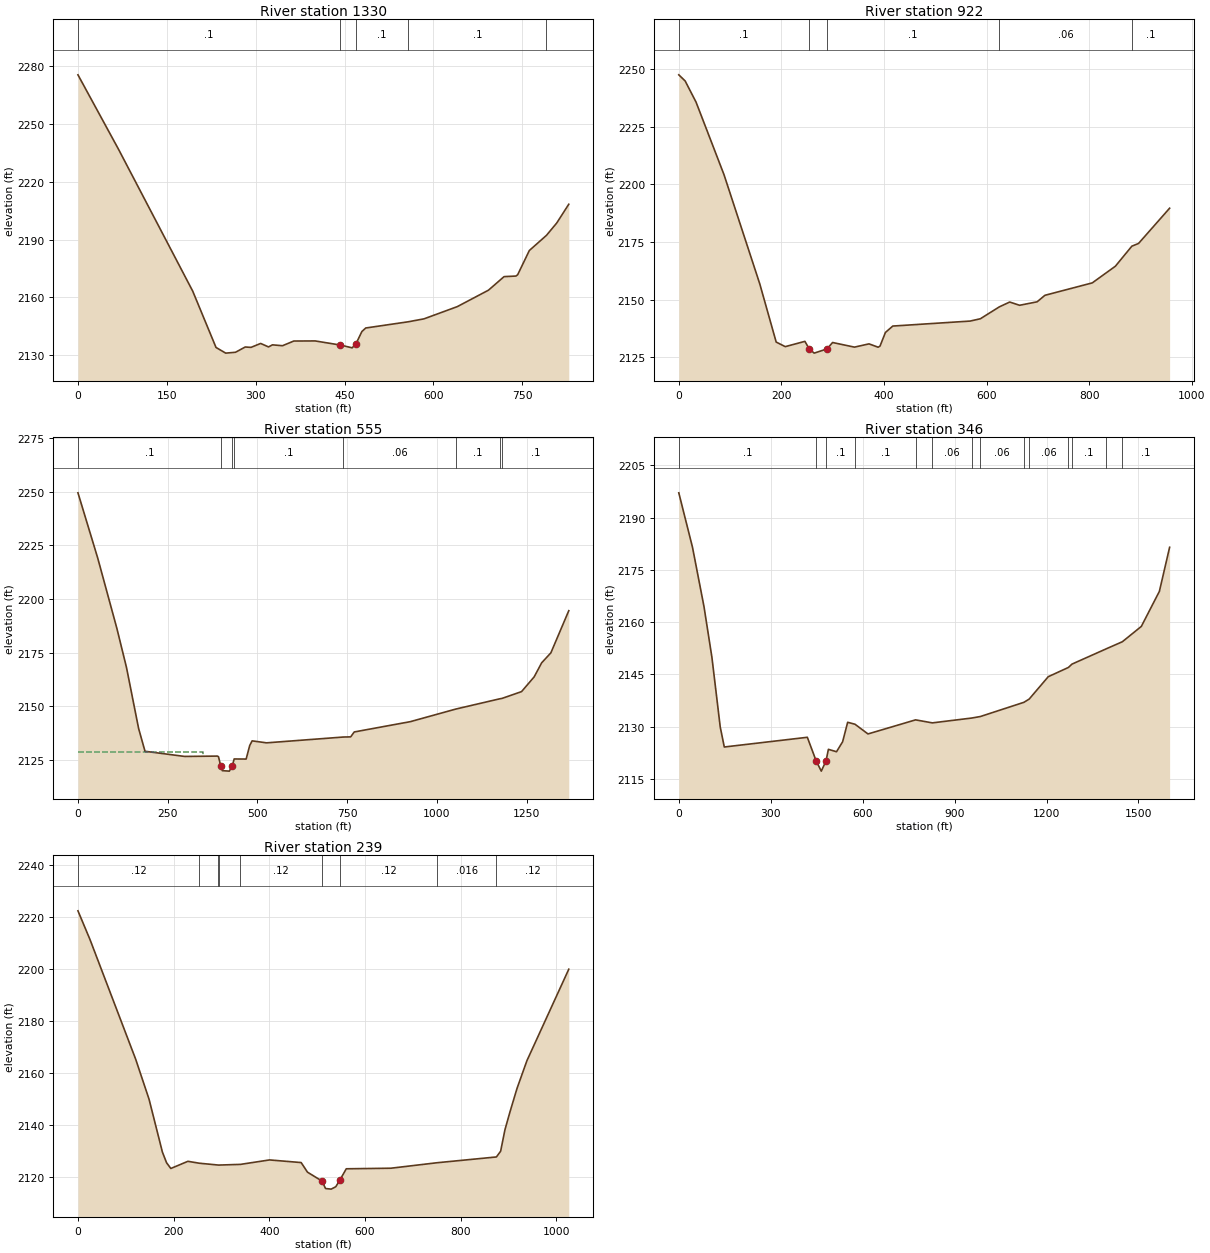
Type RM Length L Ch R = 1 ,1330    ,408.6,408.6,408.6
XS GIS Cut Line= 4
2172269.67249688264897.8475718792172260.16031796264485.019006805
2172256.35544639 264370.872859782172237.33108855264070.288005947
#Sta/Elev= 30
       0 2275.56      69 2236.58   193.7 2163.21     233 2133.97   249.4 2131.03
   265.9 2131.48   282.3 2134.21   292.1 2134.02   308.3 2136.06   321.6 2134.25
   328.2 2135.33   345.2 2134.88   364.3 2137.31   400.4 2137.36   442.9 2135.22
   462.8 2133.78   469.3 2135.95   479.2 2142.26   485.7 2144.08  557.152147.294
     584 2148.83   640.2 2155.18   692.8 2163.72   719.1 2170.75   739.2 2171.06
   742.1 2171.75   761.8 2184.33  790.662192.186   807.9 2198.56 828.334 2208.35
#Mann= 5 ,-1 , 0
       0      .1       0   442.9    .045       0   469.3      .1       0
  557.15      .1       0  790.66      .1       0
Bank Sta=442.9,469.3
XS Rating Curve= 0 ,0
Exp/Cntr(USF)=0,0
Exp/Cntr=0.3,0.1

Type RM Length L Ch R = 1 ,922     ,366.4,366.4,366.4
XS GIS Cut Line= 4
2172463.72094682264909.2621865812172549.33055709264701.896686152
2172705.33029136 264325.214400972172539.81837817264045.556340759
#Sta/Elev= 30
       0 2247.47    12.4 2244.81    33.7 2235.62    88.2 2204.17   157.9 2156.87
   189.9 2131.65   207.6 2129.67   245.9 2131.96  254.352128.677     264 2126.86
  288.892128.679   299.9 2131.46   342.5 2129.46   370.9 2130.87   388.7 2129.42
   392.3 2129.89   402.9 2135.81   417.2 2138.59   567.9 2140.75     588 2141.75
  624.852146.891   645.2    2149   664.5 2147.59   698.7  2149.1   713.9 2151.92
   806.2  2157.3   851.2 2164.51   883.42173.214   896.4 2174.38957.0157 2189.67
#Mann= 5 ,-1 , 0
       0      .1       0  254.35    .045       0  288.89      .1       0
  624.85     .06       0   883.4      .1       0
Bank Sta=254.35,288.89
XS Rating Curve= 0 ,0
Exp/Cntr(USF)=0,0
Exp/Cntr=0.3,0.1

Type RM Length L Ch R = 1 ,555     ,209.7,209.7,209.7
XS GIS Cut Line= 4
2172742.91970841265148.6637661342172883.84087757264814.628402183
2172967.34971856264402.3034998072172531.53795466264013.465458958
#Sta/Elev= 30
       0 2249.47    55.1 2219.08   108.5  2186.3   135.2 2168.15     169 2139.72
   186.8 2129.12   297.2 2126.72   388.3 2126.88   391.5 2126.61  397.672122.371
   402.1 2120.09   421.7 2119.88  429.972122.364  435.162125.544   468.5  2125.5
   478.5 2131.81   485.2 2133.97   525.4 2133.05  739.492135.755   759.7 2135.83
   769.7 2138.12     926 2142.92 1052.272148.763 1174.932153.552 1180.822153.709
  1235.7  2156.9  1270.9 2163.77  1291.8 2170.33  1317.4 2174.951367.302 2194.58
#Mann= 8 ,-1 , 0
       0      .1       0  397.67    .045       0  429.97      .1       0
  435.16      .1       0  739.49     .06       0 1052.27      .1       0
 1174.93     .06       0 1180.82      .1       0
#XS Ineff= 2 , 0
          347.88 2128.83
Permanent Ineff=
       F       F
Bank Sta=397.67,429.97
XS Rating Curve= 0 ,0
Exp/Cntr(USF)=0,0
Exp/Cntr=0.3,0.1

Type RM Length L Ch R = 1 ,346     ,106.8,106.8,106.8
XS GIS Cut Line= 5
2172847.29754663265207.702506547 2173084.7840262264887.698638047
2173150.02530822264431.0096638962172826.84677472264248.826374511
2172556.40601588263990.867496849
#Sta/Elev= 30
       0 2197.15    44.7 2181.51    82.2 2164.49     108 2149.96   135.3 2129.85
   148.5 2124.14   419.5 2126.93  448.272120.138     465 2117.21   480.4 2120.14
   488.2 2123.47   514.7 2122.78   534.6 2125.64   551.1 2131.24  574.992130.679
   617.4 2127.89  772.662131.933  827.482131.071  955.622132.455  984.042132.892
 1126.362136.979 1143.442137.907  1205.6 2144.33 1271.572146.996 1283.122147.951
 1394.492152.325 1447.642154.385  1509.4 2158.78  1568.3 2168.84 1601.71 2181.51
#Mann= 14 ,-1 , 0
       0      .1       0  448.27    .045       0   480.4      .1       0
  574.99      .1       0  772.66    .055       0  827.48     .06       0
  955.62     .05       0  984.04     .06       0 1126.36     .05       0
 1143.44     .06       0 1271.57     .05       0 1283.12      .1       0
 1394.49     .05       0 1447.64      .1       0
#XS Ineff= 2 , 0
          374.35  2125.8
Permanent Ineff=
       F       F
Bank Sta=448.27,480.4
XS Rating Curve= 0 ,0
Exp/Cntr(USF)=0,0
Exp/Cntr=0.3,0.1

Type RM Length L Ch R = 1 ,239     ,170.4,239,170.4
XS GIS Cut Line= 4
 2172855.2163387265254.4040194822173131.32933941264951.994542512
2173258.42897466264759.1537166182173372.38037178264391.003049002
#Sta/Elev= 30
       0 2222.24    25.3 2211.16   120.7 2165.28   148.6 2149.96   176.5 2129.69
   185.2 2125.59   194.1 2123.39   229.8 2126.14  253.592125.409  293.582124.701
  295.752124.707  339.562124.963   400.4 2126.67   466.5 2125.66   479.7 2121.98
   509.8  2118.6   517.5  2115.7   529.3 2115.47   538.9  2116.4   547.4 2118.95
   560.8 2123.27   653.9 2123.49  750.462125.591  874.592127.812   883.4    2130
   892.5  2138.3     903 2145.13   917.7 2154.13   938.3 2164.721025.841 2199.84
#Mann= 9 ,-1 , 0
       0     .12       0  253.59     .06       0  293.58     .12       0
  295.75     .06       0  339.56     .12       0   509.8     .04       0
   547.4     .12       0  750.46    .016       0  874.59     .12       0
#XS Ineff= 2 , 0
          411.79 2126.21
Permanent Ineff=
       F       F
Bank Sta=509.8,547.4
XS Rating Curve= 0 ,0
Exp/Cntr(USF)=0,0
Exp/Cntr=0.3,0.1
Stream Node=BIGCLEARCK      ,Main            , 0 , 0 ,Upstream end
Stream Node=BIGCLEARCK      ,Main            , 0 , 1 ,Downstream end
Stream Node=BROADRN         ,Main            , 0 , 0 ,Upstream end
Stream Node=BROADRN         ,Main            , 0 , 1 ,Downstream end
Stream Node=LAURELBR        ,Main            , 0 , 0 ,Upstream end
Stream Node=LAURELBR        ,Main            , 0 , 1 ,Downstream end
Stream Node=LAURELCK1       ,Main            , 0 , 0 ,Upstream end
Stream Node=LAURELCK1       ,Main            , 0 , 1 ,Downstream end
Stream Node=MEADOWRV3       ,Main            , 0 , 0 ,Upstream end
Stream Node=MEADOWRV3       ,Main            , 0 , 1 ,Downstream end
Stream Node=MEADOWRV4       ,Main            , 0 , 0 ,Upstream end
Stream Node=MEADOWRV4       ,Main            , 0 , 1 ,Downstream end
Stream Node=MLGNCK          ,Main            , 0 , 0 ,Upstream end
Stream Node=MLGNCK          ,Main            , 0 , 1 ,Downstream end
Stream Node=MLGNCKTR3       ,Main            , 0 , 0 ,Upstream end
Stream Node=MLGNCKTR3       ,Main            , 0 , 1 ,Downstream end
Stream Node=MLGNCKTR4       ,Main            , 0 , 0 ,Upstream end
Stream Node=MLGNCKTR4       ,Main            , 0 , 1 ,Downstream end
Stream Node=MUDDYCK         ,Main            , 0 , 0 ,Upstream end
Stream Node=MUDDYCK         ,Main            , 0 , 1 ,Downstream end
Stream Node=SECONDCK        ,Main            , 0 , 0 ,Upstream end
Stream Node=SECONDCK        ,Main            , 0 , 1 ,Downstream end
Stream Node=TUCKHORN        ,Main            , 0 , 0 ,Upstream end
Stream Node=TUCKHORN        ,Main            , 0 , 1 ,Downstream end
Stream Node=TUCKHORNT2      ,Main            , 0 , 0 ,Upstream end
Stream Node=TUCKHORNT2      ,Main            , 0 , 1 ,Downstream end
LCMann Table=0

Chan Stop Cuts=-1
Use User Specified Reach Order=0
Composite Channel Slope=5